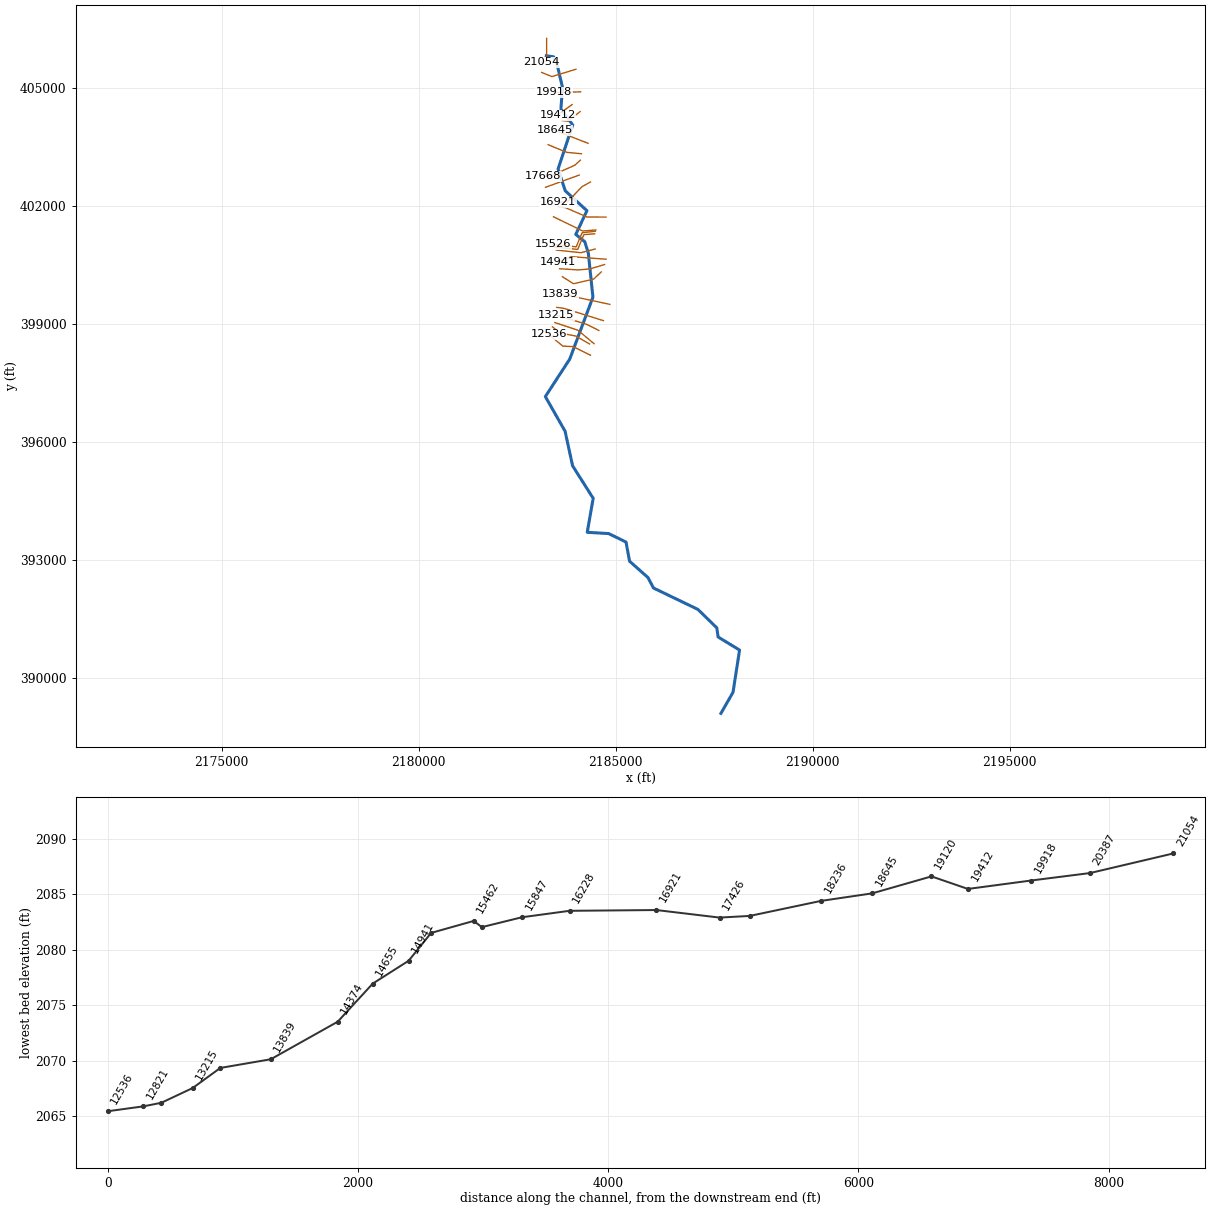
--- LCSTCK.prj (project) ---

Proj Title=LCSTCK
Current Plan=p01
Default Exp/Contr=0,0
English Units
Geom File=g01
Flow File=f01
Plan File=p01
Background Map Layer=Inundation Boundary (01pct Value_0)
BEGIN DESCRIPTION:
----------MODEL BY WOOD PLC 2021----------
Stream Name: Locust Creek
Flood Zone: Enhanced Approximate
Pocahontas County, WV
HEC-RAS Version: RAS 6.1
Vertical Datum: NAVD88
Projection: NAD 1983 StatePlane West Virginia S FIPS 4702 (US Feet)
Terrain: 1-meter LIDAR (FEMA Region III 3DEP collected 2016-2018)
Land Use: 2019 NLCD
Hydrologic Method:
WV SIR2010-5033 regression equations
Model Notes:
None.
END DESCRIPTION:
DSS Export Rating Curves= 0
DSS Export Rating Curve Sorted= 0
DSS Export Volume Flow Curves= 0
DXF OffsetX= 0
DXF OffsetY= 0
DXF ScaleX= 0
DXF ScaleY= 0

--- LCSTCK.p01 (plan) ---

Plan Title=Floodplain
Program Version=6.00
Short Identifier=Floodplain
Geom File=g01
Flow File=f01
Subcritical Flow
K Sum by GR= 0
Std Step Tol= 0.01
Critical Tol= 0.01
Num of Std Step Trials= 20
Max Error Tol= 0.3
Flow Tol Ratio= 0.001
Split Flow NTrial= 30
Split Flow Tol= 0.02
Split Flow Ratio= 0.02
Log Output Level= 0
Friction Slope Method= 1
Unsteady Friction Slope Method= 2
Unsteady Bridges Friction Slope Method= 1
Parabolic Critical Depth
Global Vel Dist= 0 , 0 , 0
Global Log Level= 0
CheckData=False
Encroach Param=-1 ,0,0, 0
Mapping Interval=1HOUR
Computation Time Step Use Courant=        0
Computation Time Step Use Time Series=    0
Computation Time Step Count To Double=0
Computation Time Step Max Doubling=0
Computation Time Step Max Halving=0
Computation Time Step Residence Courant=0
Run HTab= 0
Run UNet= 0
Run Sediment= 0
Run PostProcess= 0
Run WQNet= 0
Run RASMapper=-1
UNET Theta= 0
UNET Theta Warmup= 0
UNET ZTol= 0
UNET ZSATol= 0
UNET MxIter= 0
UNET Max Iter WO Improvement= 0
UNET MaxInSteps= 0
UNET DtIC= 0
UNET DtMin= 0
UNET MaxCRTS= 0
UNET WFStab= 0
UNET SFStab= 0
UNET WFX= 1
UNET SFX= 1
UNET Gravity=32.174
UNET 1D Methodology=Finite Difference
UNET DSS MLevel= 1
UNET Pardiso=0
UNET DZMax Abort= 0
UNET Use Existing IB Tables= 0
UNET Froude Reduction=False
UNET Froude Limit= 0
UNET Froude Power= 0
UNET D1 Cores= 0
UNET WindReference=Eulerian
UNET WindDragFormulation=Hsu (1988)
UNET D2 Coriolis=0
UNET D2 Cores= 0
UNET D2 Theta= 1
UNET D2 Theta Warmup= 1
UNET D2 Z Tol= 0.01
UNET D2 Volume Tol= 0.01
UNET D2 Max Iterations= 20
UNET D2 Equation= 0
UNET D2 RampUpFraction=0.1
UNET D2 TimeSlices= 1
UNET D2 Turbulence Formulation=Non-Conservative (original)
UNET D2 Eddy Viscosity=0.3
UNET D2 Transverse Eddy Viscosity=0.1
UNET D2 Smagorinsky Mixing=0
UNET D2 BCVolumeCheck=0
UNET D2 Cores=0
UNET D2 SolverType=PARDISO (Direct)
UNET D2 Minimum Iterations= 2147483647
UNET D2 Maximum Iterations= 2147483647
UNET D2 Restart Number= 10
UNET D2 Relaxation Coeff=1.3
UNET D2 SOR Precondition Iterations= 10
UNET D2 ILUT Maximum Fill= 8
UNET D2 ILUT Tolerance=1E-08
UNET D1D2 MaxIter= 0
UNET D1D2 ZTol=0.01
UNET D1D2 QTol=0.1
UNET D1D2 MinQTol=1
Write IC File= 0
Write IC File at Fixed DateTime=0
Write IC File at Sim End=0
Echo Input=False
Echo Parameters=False
Echo Output=False
Write Detailed= 0
HDF Write Warmup=0
HDF Write Time Slices=0
HDF Flush=0
HDF Compression= 1
HDF Chunk Size= 1
HDF Spatial Parts= 1
HDF Use Max Rows=0
HDF Fixed Rows= 1
Calibration Method= 0
Calibration Iterations= 20
Calibration Max Change=0.05
Calibration Tolerance=0.2
Calibration Maximum=1.5
Calibration Minimum=0.5
Calibration Optimization Method= 1
WQ AD Non Conservative
WQ ULTIMATE=-1
WQ Max Comp Step=1HOUR
WQ Output Interval=15MIN
WQ Output Selected Increments= 0
WQ Output face flow=0
WQ Output face velocity=0
WQ Output face area=0
WQ Output face dispersion=0
WQ Output cell volume=0
WQ Output cell surface area=0
WQ Output cell continuity=0
WQ Output cumulative cell continuity=0
WQ Output face conc=0
WQ Output face dconc_dx=0
WQ Output face courant=0
WQ Output face peclet=0
WQ Output face adv mass=0
WQ Output face disp mass=0
WQ Output cell mass=0
WQ Output cell source sink temp=0
WQ Output nsm pathways=0
WQ Output nsm derived pathways=0
WQ Create Restart=0
WQ Fixed Restart=0
WQ System Summary=0
WQ Write To DSS=0
Sorting and Armoring Iterations= 10
XS Update Threshold= 0.02
Bed Roughness Predictor= 0
Hydraulics Update Threshold= 0.02
Energy Slope Method= 1
Volume Change Method= 1
Sediment Retention Method= 0
Sediment TS Multiplier= 1
Warm Up Method= 0
XS Weighting Method= 0
Number of US Weighted Cross Sections= 1
Number of DS Weighted Cross Sections= 1
Upstream XS Weight=0
Main XS Weight=1
Downstream XS Weight=0
Number of DS XS's Weighted with US Boundary= 1
Upstream Boundary Weight= 1
Weight of XSs Associated with US Boundary= 0
Number of US XS's Weighted with DS Boundary= 1
Downstream Boundary Weight= 0.5
Weight of XSs Associated with DS Boundary= 0.5
Percentile Method= 0
Sediment Output Level= 3
Mass or Volume Output= 0
Output Increment Type= 1
Profile and TS Output Increment= 1
Transport Output Increment 1
XS Output Flag= 0
XS Output Increment= 10
Read HDF5 Sediment Hotstart= 0
Sediment Hotstart Type= 0
Write Gradation File= 0
Read Gradation Hotstart= 0
Write HDF5 File= 1
Write Binary Output= 1
Write DSS Sediment File= 0
DSS Sediment Output Type= 1
SV Curve= 0
Specific Gage Flag= 0
Subcell Erosion Methods= 0
Subcell Deposition Methods= 0
Advection Scheme= 1
Matrix Solver= 0
Implicit Weighting Factor= 1
Maximum Outer Loop Convergence Iterations= 5
Convergence Maximum Absolute= 0.001
Convergence RMSE= 0.0001
Grain Fractions Max Abs Error= 0.001
Max Subgrid Regions= 1
Max Subgrid Length Scale= 3.402823E+38
Initial Layer Thickness= 3.402823E+38
Min Layer Thickness= 3.402823E+38
Max Layer Thickness= 3.402823E+38
Number of Layers= 5

--- LCSTCK.f01 (steady flow) ---

Flow Title=Flow
Program Version=6.10
Number of Profiles= 6
Profile Names=01pct,10pct,04pct,02pct,0_2pct,01plus
River Rch & RM=LCSTCK,Main            ,21054
    1930    1070    1390    1650    2630    2850
River Rch & RM=LCSTCK,Main            ,14655
    2160    1200    1560    1850    2940    3190
River Rch & RM=LCSTCK,Main            ,9070
    2430    1360    1760    2080    3300    3590
River Rch & RM=LCSTCK,Main            ,1720
    2920    1640    2120    2500    3950    4310
Boundary for River Rch & Prof#=LCSTCK,Main            , 1
Up Type= 0
Dn Type= 3
Dn Slope=0.00944
Boundary for River Rch & Prof#=LCSTCK,Main            , 2
Up Type= 0
Dn Type= 3
Dn Slope=0.00944
Boundary for River Rch & Prof#=LCSTCK,Main            , 3
Up Type= 0
Dn Type= 3
Dn Slope=0.00944
Boundary for River Rch & Prof#=LCSTCK,Main            , 4
Up Type= 0
Dn Type= 3
Dn Slope=0.00944
Boundary for River Rch & Prof#=LCSTCK,Main            , 5
Up Type= 0
Dn Type= 3
Dn Slope=0.00944
Boundary for River Rch & Prof#=LCSTCK,Main            , 6
Up Type= 0
Dn Type= 3
Dn Slope=0.00944
DSS Import GetInterval= 0
DSS Import GetPeak= 0
DSS Import FillOption= 0

--- LCSTCK.g01 (geometry) ---

Geom Title=Geometry
Program Version=6.00

River Reach=LCSTCK          ,Main
Reach XY= 30
     2183240.172      405816.855     2183424.269      405790.777
2183516.46585401405581.703669698     2183650.275      405011.953
      2183610.06      404464.7532183909.35061404404060.494142478
     2183538.321       402941.552183719.67126232402387.352398209
2184270.64628537401880.934415048     2183987.105      401279.413
2184216.30303534 401092.68317022     2184305.547      400807.244
     2184422.676      399685.959     2183834.985      398113.015
     2183214.812      397159.104      2183715.74      396279.992
2183906.50057975395400.584169903     2184429.108      394575.652
     2184278.499      393711.7912184824.04876134393679.515515213
2185262.89282893393463.645509709     2185353.058      392977.369
2185821.72129385392561.131713678     2185958.457      392297.778
2187087.72601634 391753.37409933       2187566.7       391285.81
     2187600.456       391052.68     2188144.939      390720.693
     2187979.057      389648.163     2187671.612      389112.441

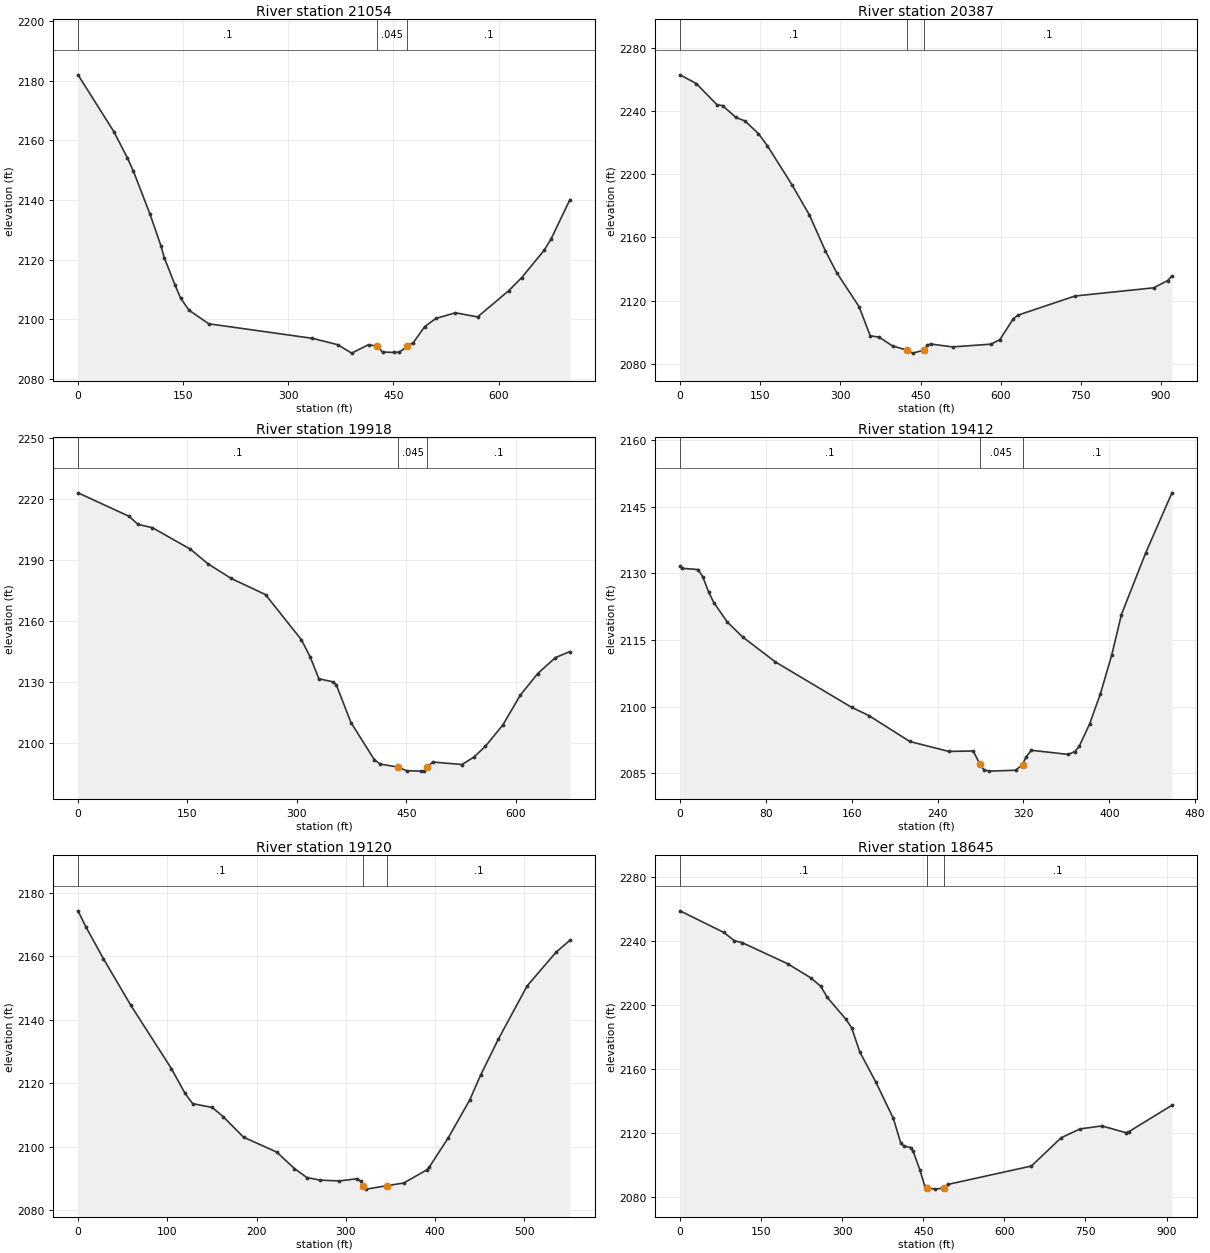
Type RM Length L Ch R = 1 ,21054   ,666.9,666.9,666.9
XS GIS Cut Line= 3
2183247.41850125406259.6086861572183247.79775201405689.589489326
2183122.89969311405647.813202315
#Sta/Elev= 30
       0 2181.95    51.2 2162.88    70.4 2154.13    79.1 2149.61   102.4 2135.44
   118.4 2124.56   123.1 2120.65   138.4 2111.48   146.4 2107.07   158.4 2103.04
   186.4  2098.5   334.4 2093.62   370.4 2091.49   390.4 2088.66   414.4 2091.49
   426.9 2090.97   434.4 2089.03   450.9 2088.89   458.4 2088.99     470 2090.98
   478.4 2092.21   494.4 2097.51   510.4 2100.27   538.4 2102.19     570  2100.8
   614.3 2109.57   632.9 2113.97   664.9 2123.12   675.1 2127.05   701.7 2140.12
#Mann= 3 ,0,0
       0      .1       0   426.9    .045       0     470      .1       0
Bank Sta=426.9,470
XS Rating Curve= 0 ,0
Exp/Cntr=0.3,0.1

Type RM Length L Ch R = 1 ,20387   ,474.8,469.9,462
XS GIS Cut Line= 3
2183992.38916839405475.0031481912183381.18780614405288.033034531
2183120.89112318405394.188303967
#Sta/Elev= 30
       0 2262.81    30.5 2257.28    68.9 2243.96    79.7 2243.31   104.8 2235.84
   121.5 2233.66   146.6 2225.67   163.4 2218.02   209.4 2193.31   241.9 2174.33
   272.1 2151.42     293 2137.83   334.9 2116.32   355.8 2097.88   372.5 2096.99
   397.6 2091.43   424.4 2088.81   435.3 2086.89   456.5  2088.8   462.9 2091.98
   468.7 2092.66   509.8 2090.83   581.7 2092.55   598.4 2095.44   623.5 2108.59
   631.9 2110.85     739    2123   886.3 2128.18   912.4 2132.79   920.3 2135.68
#Mann= 3 ,0,0
       0      .1       0   424.4    .045       0   456.5      .1       0
Bank Sta=424.4,456.5
XS Rating Curve= 0 ,0
Exp/Cntr=0.3,0.1

Type RM Length L Ch R = 1 ,19918   ,486.7,506,516.7
XS GIS Cut Line= 2
2184110.10608402404900.4087496462183436.25807751404884.320571711
#Sta/Elev= 30
       0 2223.14      70 2211.59      82 2207.65     102 2205.97     154 2195.42
     178 2188.23     210    2181   256.9 2173.07   306.1 2150.86   318.4 2142.21
     330 2131.68     350  2130.1     354 2128.59     374 2110.14     406 2091.85
     414 2089.72   438.8 2088.18   450.1 2086.42   470.1 2086.22   474.1 2086.32
   477.9 2088.18   486.1 2090.69   526.1 2089.48   542.1 2093.02   558.1 2098.41
   582.1 2108.91   606.1 2123.65   629.9 2134.23   654.1 2142.07     674 2145.06
#Mann= 3 ,0,0
       0      .1       0   438.8    .045       0   477.9      .1       0
Bank Sta=438.8,477.9
XS Rating Curve= 0 ,0
Exp/Cntr=0.3,0.1

Type RM Length L Ch R = 1 ,19412   ,284.4,291.3,287.1
XS GIS Cut Line= 2
 2183893.8004288404577.1273102362183521.94974961404309.001065871
#Sta/Elev= 30
       0 2131.63       2 2131.15    16.8 2130.88    21.2 2129.26    26.7 2125.79
    31.6  2123.4    44.1 2119.04    58.4 2115.68    88.8 2110.07   159.8 2099.85
   175.9 2097.99   214.1 2092.14   250.4  2089.9   273.2    2090  279.65 2086.96
   283.1 2085.77     288 2085.46   312.7 2085.66   319.2 2086.92   322.5  2088.7
   327.5 2090.16     362 2089.22   367.9 2089.88   371.9 2091.01   381.7 2096.09
   391.6 2102.77   402.3  2111.6   411.3 2120.71   433.8 2134.53   458.4 2148.16
#Mann= 3 ,0,0
       0      .1       0  279.65    .045       0   319.2      .1       0
Bank Sta=279.65,319.2
XS Rating Curve= 0 ,0
Exp/Cntr=0.3,0.1

Type RM Length L Ch R = 1 ,19120   ,484.9,474.8,441.7
XS GIS Cut Line= 3
2184098.58248416404399.0440098882183786.72895545 404155.25375133
2183632.62167925404172.419063002
#Sta/Elev= 30
       0 2174.35     8.7 2169.35    28.4 2159.28    58.9 2144.67   104.6 2124.59
   119.8 2116.83   128.4 2113.55   150.3 2112.34   162.6 2109.45   185.4 2102.97
   222.5 2098.28   242.4 2093.08   256.3 2090.25   270.9 2089.43   292.5 2089.17
   312.8 2089.87   316.5 2089.06   319.3 2087.65   322.9 2086.59  346.23 2087.69
   364.9 2088.53   390.6 2092.66   393.4 2093.54   414.7 2102.79   438.7  2114.7
   450.9 2122.56   470.9 2133.96     503 2150.68   535.2 2161.24   550.9 2165.07
#Mann= 3 ,0,0
       0      .1       0   319.3    .045       0  346.23      .1       0
Bank Sta=319.3,346.23
XS Rating Curve= 0 ,0
Exp/Cntr=0.3,0.1

Type RM Length L Ch R = 1 ,18645   ,409.8,409.5,409
XS GIS Cut Line= 2
2184297.92630848 403593.978748542183449.95730848 403924.20474854
#Sta/Elev= 30
       0 2258.74    81.1 2245.24   100.6 2240.09     115 2238.88   199.3 2225.69
   242.3 2216.81   260.3 2211.67   272.6 2204.65   306.7 2191.15   317.5 2185.74
   332.4 2170.82   362.5  2151.7   394.6  2129.2   408.5 2113.74     414 2111.99
   426.8 2111.02   431.1 2108.83     444 2096.81   452.6 2087.12   456.9 2085.89
   471.8 2085.06   488.9  2085.8   495.5    2088   650.1 2099.48   705.1 2117.14
   740.2 2122.65   780.4  2124.5   824.5 2120.33   830.4 2120.95     910  2137.4
#Mann= 3 ,-1,0
       0      .1       0   456.9    .045       0   488.9      .1       0
Bank Sta=456.9,488.9
XS Rating Curve= 0 ,0
Exp/Cntr=0.3,0.1

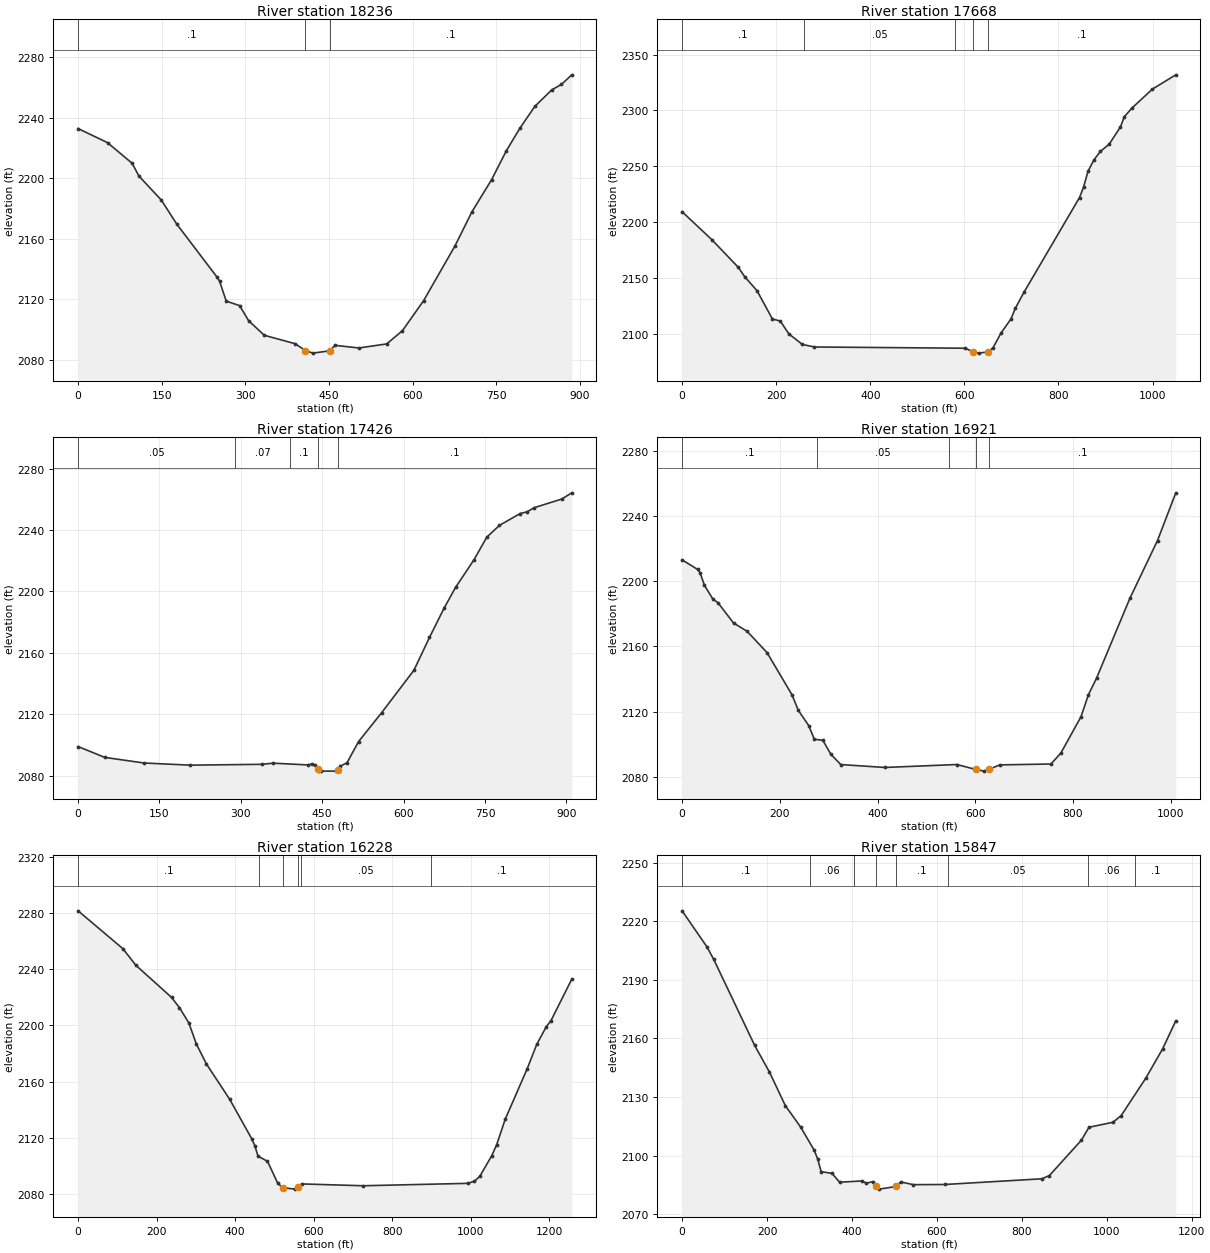
Type RM Length L Ch R = 1 ,18236   ,552.2,568.2,586.8
XS GIS Cut Line= 3
  2184132.718895403327.9449368762183761.00340206403363.198355373
2183286.89184459403556.876338403
#Sta/Elev= 30
       0 2232.85    52.8 2223.52      97 2209.86     109 2201.49   149.2  2185.6
   177.3 2169.51   249.7 2134.38   253.7 2131.98   265.7 2118.75   289.8 2115.78
   305.9 2105.77     334 2096.18   389.2 2090.62   407.8 2086.06   420.9 2084.38
   451.6 2085.91   460.7 2089.53   503.9 2087.79   553.5 2090.47   581.7  2099.2
   619.7 2119.05   676.2 2155.41   706.5 2177.87   741.6 2199.02   768.2 2218.22
   792.7 2233.24   819.3 2247.53   849.6 2258.44   866.9 2262.03   885.5 2268.37
#Mann= 3 ,-1,0
       0      .1       0   407.8    .045       0   451.6      .1       0
Bank Sta=407.8,451.6
XS Rating Curve= 0 ,0
Exp/Cntr=0.3,0.1

Type RM Length L Ch R = 1 ,17668   ,242.9,241.5,239.7
XS GIS Cut Line= 4
2184102.40770839403163.9541595462183962.65705971403036.355741191
2183332.76645482402754.8290721232183162.63523035402750.778328683
#Sta/Elev= 30
       0 2209.46      63 2184.55   119.6 2159.67     133  2151.4   159.3 2138.83
     192 2113.53   208.7 2111.73   226.8 2100.29   255.8 2090.76   281.3 2088.53
   602.3 2087.41   617.92084.235   630.1 2083.03   650.12084.148   660.8 2087.74
     678 2101.08   699.2 2113.67   708.3 2123.08   726.5  2137.3   844.8 2222.17
   853.3 2231.32   862.7  2245.5   875.4 2255.79   889.2 2263.38   907.8 2269.83
   931.8 2285.28   939.8 2294.28   955.6 2301.88   999.8 2319.12  1049.4 2331.85
#Mann= 5 ,-1,0
       0      .1       0  259.24     .05       0  579.24      .1       0
   617.9    .045       0   650.1      .1       0
Bank Sta=617.9,650.1
XS Rating Curve= 0 ,0
Exp/Cntr(USF)=0,0
Exp/Cntr=0.3,0.1

Type RM Length L Ch R = 1 ,17426   ,490.1,505,507.9
XS GIS Cut Line= 3
 2184074.1981964402786.065569719 2183646.4711964402630.907569719
 2183218.7431964402475.748569719
#Sta/Elev= 30
       0  2098.9    49.1 2091.83   121.3 2088.19   206.4 2086.77   338.3 2087.32
   359.6 2088.06   423.4 2086.94   431.9 2087.64   436.2 2086.85  441.36 2084.03
   444.7 2082.93   448.3 2082.88   474.5 2082.91   478.7 2083.94   483.1 2086.09
   495.7 2088.35     517 2102.15   559.6 2121.01   619.1 2148.68   647.7 2170.05
   674.4 2188.95   695.7  2202.6   729.9 2220.74   753.3 2235.37   776.6 2243.04
   814.9 2250.79   827.6 2251.89   840.4 2254.55   891.5 2260.22     910 2264.27
#Mann= 5 ,-1,0
       0     .05       0     290     .07       0     390      .1       0
  441.36    .045       0   478.7      .1       0
Bank Sta=441.36,478.7
XS Rating Curve= 0 ,0
Exp/Cntr=0.3,0.1

Type RM Length L Ch R = 1 ,16921   ,730.8,693.6,677.1
XS GIS Cut Line= 4
2184360.13808652402610.8941498022184145.40429077402491.614819742
2183797.19591703 402127.148819162183539.09269301402091.729612006
#Sta/Elev= 30
       0 2213.04      32 2207.17    36.6 2205.31    45.7 2197.51      63 2189.02
    73.2 2186.88   105.2 2174.36   132.7 2169.36   173.8 2156.23   224.8  2130.4
   237.9 2120.76     259 2111.53   270.6 2103.12     288 2102.45   304.3 2093.95
   324.6 2087.58   415.2 2085.81   562.3 2087.61600.66672084.617     618 2083.56
628.36592084.696     650 2087.38   754.8 2087.93     775 2094.62   816.3 2116.95
   831.5 2130.46   848.2 2140.65   916.3 2189.51   972.8 2224.93  1010.2 2254.16
#Mann= 5 ,-1,0
       0      .1       0  275.64     .05       0  545.64      .1       0
600.6667    .045       0628.3659      .1       0
Bank Sta=600.6667,628.3659
XS Rating Curve= 0 ,0
Exp/Cntr=0.3,0.1

Type RM Length L Ch R = 1 ,16228   ,379.2,380.7,380.7
XS GIS Cut Line= 4
2184754.13007307401719.3806293422184276.01385597401721.043826141
2183720.50612524 401960.544165142183547.53365819401980.502526723
#Sta/Elev= 30
       0 2281.43     114 2254.51   147.2 2242.68     238 2219.84     258 2212.57
     282  2201.7   301.2 2186.69   326.6 2172.59     386  2147.4     442 2119.38
     450 2114.44   458.2 2106.92   482.3 2103.27   508.5 2087.63   520.7 2084.53
     552 2083.49   559.3 2084.82   569.4 2087.19   726.2 2085.89   991.9  2087.6
  1009.4 2089.09  1022.9  2092.6  1053.4 2107.25    1066 2115.12  1087.5 2133.11
  1143.8  2169.2  1167.9 2186.43  1192.1 2198.94  1204.2 2203.35  1257.2 2232.85
#Mann= 6 ,-1,0
       0      .1       0     460     .06       0   520.7    .045       0
   559.3     .06       0  568.12     .05       0  898.12      .1       0
Bank Sta=520.7,559.3
XS Rating Curve= 0 ,0
Exp/Cntr(USF)=0,0
Exp/Cntr=0.3,0.1

Type RM Length L Ch R = 1 ,15847   ,280.2,321,356.1
BEGIN DESCRIPTION:
structure xs 4
END DESCRIPTION:
XS GIS Cut Line= 3
2184498.54466143401391.8409588972184163.78126453401365.736931701
2183420.44544396401727.461414688
#Sta/Elev= 30
       0  2225.3    58.5 2206.87    74.6 2200.41   170.9 2156.43   205.7 2142.81
   243.1 2125.63   279.2 2114.65   311.3 2102.75   319.3 2098.26   327.4 2091.86
   353.1 2090.97   370.9 2086.44   424.3  2087.1   433.8 2085.89   448.8 2086.76
   457.4 2084.29   464.3 2082.91503.99412084.271   514.6 2086.61   544.5 2085.19
   617.9 2085.28   846.9 2088.19   864.7 2089.81   940.3 2107.97   958.1 2114.56
  1014.3  2117.1  1033.8 2120.49  1091.6  2139.6  1131.6 2154.73  1162.5 2169.02
#Mann= 8 ,-1,0
       0      .1       0     300     .06       0  405.78      .1       0
   457.4    .045       0503.9941      .1       0  625.78     .05       0
  955.78     .06       0 1065.78      .1       0
Bank Sta=457.4,503.9941
XS Rating Curve= 0 ,0
Exp/Cntr=0.5,0.3

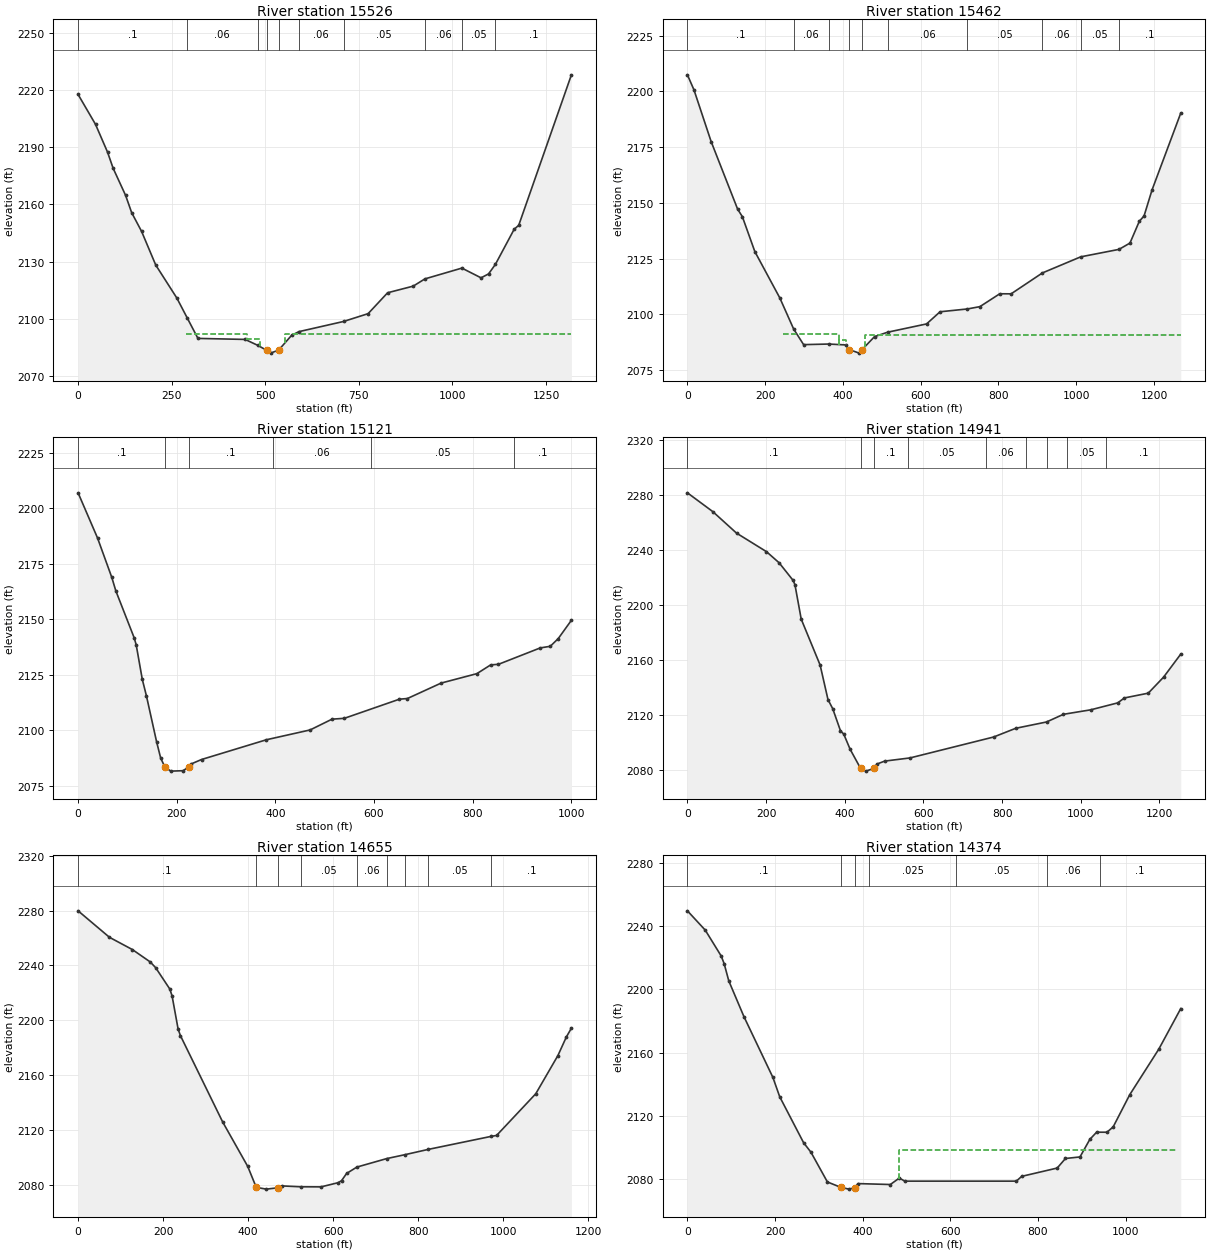
Type RM Length L Ch R = 1 ,15526   ,62.4,64.3,62
BEGIN DESCRIPTION:
structure xs 3; 17.5 ft between xs & structure
END DESCRIPTION:
XS GIS Cut Line= 4
2184482.35122084 401358.447208942184147.99344401401321.003595984
2183998.16995965400963.3107773922183408.24796325401030.094399625
#Sta/Elev= 30
       0 2217.72    46.6 2202.03    78.7 2187.45    93.6 2179.02     127 2164.75
   143.1 2155.73   169.6  2145.9   207.5 2128.22   263.8 2110.93   291.1 2100.65
   320.2 2089.74   446.2 2089.21   479.4 2086.16  503.49 2083.54   514.1 2082.02
   535.7 2083.59   570.4 2091.36   589.9 2093.29   709.2 2098.63   774.8 2102.73
   826.9 2113.69   895.3 2117.17   926.6 2120.97  1025.3 2126.63  1076.5 2121.52
  1096.6 2123.59  1114.7 2128.54    1165 2147.02  1177.1 2149.07  1317.9 2228.02
#Mann= 10 ,-1,0
       0      .1       0   291.1     .06       0   479.4     .07       0
  503.49    .045       0   535.7     .07       0   589.9     .06       0
   709.2     .05       0   926.6     .06       0  1025.3     .05       0
  1114.7      .1       0
#XS Ineff= 4 ,-1
  288.38     450    2092   552.7  1317.9 2091.99     450     486  2089.5
       0  288.38  2089.5
Permanent Ineff=
       F       F       F       F
Bank Sta=503.49,535.7
XS Rating Curve= 0 ,0
Exp/Cntr(USF)=0,0
Exp/Cntr=0.5,0.3

Type RM Length L Ch R = 1 ,15462   ,365.7,340.6,325.4
BEGIN DESCRIPTION:
structure xs 2; 21.8 ft between xs & structure
END DESCRIPTION:
XS GIS Cut Line= 4
2184464.99581678401294.7269543522184192.29602599401272.465746941
2184036.46757412400897.7354221862183450.25577896 400957.09864195
#Sta/Elev= 30
       0 2207.48    16.9 2200.71      61 2177.52   129.2 2147.17   141.3 2143.82
   173.4 2128.15   237.6 2107.36   273.1 2093.44   298.8 2086.39   363.8 2086.66
   407.1 2086.26   415.8 2084.19   441.8 2082.58  449.19 2084.15   481.2 2089.99
   514.9 2091.97   615.1 2095.69   649.7 2101.14   719.9  2102.4   752.1 2103.44
   803.3 2109.22   832.5 2109.19   912.9 2118.57  1011.4 2125.79  1109.8 2129.14
  1138.1 2131.97  1162.2 2141.77  1174.3 2144.13  1194.8 2155.78  1268.7  2190.3
#Mann= 10 ,-1,0
       0      .1       0   273.1     .06       0   363.8      .1       0
   415.8    .045       0  449.19      .1       0   514.9     .06       0
   719.9     .05       0   912.9     .06       0  1011.4     .05       0
  1109.8      .1       0
#XS Ineff= 3 ,-1
  245.93     390    2091     456  1268.7  2090.6     390     408 2088.54
Permanent Ineff=
       F       F       F
Bank Sta=415.8,449.19
XS Rating Curve= 0 ,0
Exp/Cntr(USF)=0,0
Exp/Cntr=0.5,0.3

Type RM Length L Ch R = 1 ,15121   ,187.7,180.1,171.1
BEGIN DESCRIPTION:
structure xs 1
END DESCRIPTION:
XS GIS Cut Line= 3
2184478.30713221400907.6449051582184115.72365383400814.534344245
2183493.52602326 400881.35486443
#Sta/Elev= 30
       0 2206.85    39.4 2186.52    68.3 2168.78    76.5 2162.71   113.7 2141.55
   117.8  2138.4   130.2 2122.79   138.5 2115.45   159.1 2094.78   167.4 2087.42
   175.7 2083.46   187.8  2081.5   212.8 2081.69   223.9 2083.31   229.3 2084.74
   250.2 2086.73   381.9 2095.64   470.4 2100.05   514.7  2104.9   539.8 2105.29
   651.5 2113.91   667.6  2114.2     736 2121.16   808.4  2125.4   836.5 2129.36
   852.2 2129.61   937.1 2137.01   957.2 2137.72   973.3 2141.17  1000.1 2149.45
#Mann= 6 ,-1,0
       0      .1       0   175.7    .045       0   223.9      .1       0
  394.35     .06       0  594.35     .05       0  884.35      .1       0
Bank Sta=175.7,223.9
XS Rating Curve= 0 ,0
Exp/Cntr(USF)=0,0
Exp/Cntr=0.3,0.1

Type RM Length L Ch R = 1 ,14941   ,283.2,286.3,289.7
XS GIS Cut Line= 3
2184756.67439309400649.3678149652183874.59472016400713.462866894
2183531.46152954400575.465709022
#Sta/Elev= 30
       0 2281.68    64.7 2267.96   124.8 2252.35     201 2238.83   233.1 2230.74
   268.9 2217.83   273.4 2214.73   289.3  2189.7   337.4 2156.23   357.4 2131.06
   369.5 2124.43   389.1 2108.39   397.5 2105.93   413.6 2094.95  440.22 2080.98
   453.7 2078.99   473.7 2080.94   481.8 2084.13   501.3 2086.28     566 2088.61
   778.5 2103.84   834.7 2110.19   912.9 2114.78     956 2120.38  1025.3 2123.64
    1094  2128.7  1110.9 2132.29  1171.6 2135.77  1210.4 2147.39  1254.2  2164.2
#Mann= 9 ,-1,0
       0      .1       0  440.22    .045       0   473.7      .1       0
     560     .05       0     760     .06       0     860      .1       0
  914.41     .06       0  964.41     .05       0 1064.41      .1       0
Bank Sta=440.22,473.7
XS Rating Curve= 0 ,0
Exp/Cntr=0.3,0.1

Type RM Length L Ch R = 1 ,14655   ,277.8,280.9,284
XS GIS Cut Line= 4
2184718.97908911400513.1720289272184340.62444757400401.011562067
2184044.52081506400377.0839958042183576.43780003400406.993453633
#Sta/Elev= 30
       0 2279.82    73.8 2260.52   127.8 2251.57   169.8 2242.55   182.5 2238.38
   215.7 2222.86   221.1  2217.9   235.4 2193.54   240.7  2188.9   340.1 2125.95
   399.1 2093.53   419.2  2078.2   443.2 2076.94   471.3 2077.96   479.4 2079.28
   523.5 2078.65   571.7 2078.58   611.8 2081.64   619.8 2083.08   631.8 2088.38
   655.9 2093.01     726 2099.19     769 2102.05   824.3 2105.93   972.6 2115.44
   984.6 2116.06  1076.8 2146.46  1128.9  2174.3    1149 2187.99  1160.7 2194.28
#Mann= 9 ,-1,0
       0      .1       0   419.2    .045       0   471.3      .1       0
   523.5     .05       0   655.9     .06       0     726      .1       0
     769     .06       0   824.3     .05       0   972.6      .1       0
Bank Sta=419.2,471.3
XS Rating Curve= 0 ,0
Exp/Cntr(USF)=0,0
Exp/Cntr=0.3,0.1

Type RM Length L Ch R = 1 ,14374   ,543.6,534.9,524.2
XS GIS Cut Line= 4
2184633.70057454 400326.138231282184442.25993923400144.565669953
2183929.18851877400026.0486405832183645.82333377400204.980809662
#Sta/Elev= 30
       0 2249.85    40.7 2237.61      77 2221.26    83.8 2216.39    94.4 2205.45
   128.9 2182.84   195.1 2144.24   210.6 2132.02   265.1 2102.89   281.8 2096.92
   319.4 2078.04  350.32  2074.6   368.5  2073.5   382.22074.485   389.2 2077.01
     463 2076.42   483.6 2080.53   495.9 2078.56   750.4 2078.56   762.7 2081.59
   843.7 2086.86   862.6 2092.92   895.7 2093.89   918.1    2105   933.6 2109.58
   957.2 2109.56   971.4 2112.93  1009.2 2133.32  1075.5 2162.19  1125.6  2187.9
#Mann= 7 ,-1,0
       0      .1       0  350.32    .045       0   382.2      .1       0
  413.85    .025       0  613.85     .05       0  820.43     .06       0
  940.43      .1       0
#XS Ineff= 1 ,-1
  482.03  1115.3 2098.25
Permanent Ineff=
       F
Bank Sta=350.32,382.2
XS Rating Curve= 0 ,0
Exp/Cntr(USF)=0,0
Exp/Cntr=0.3,0.1

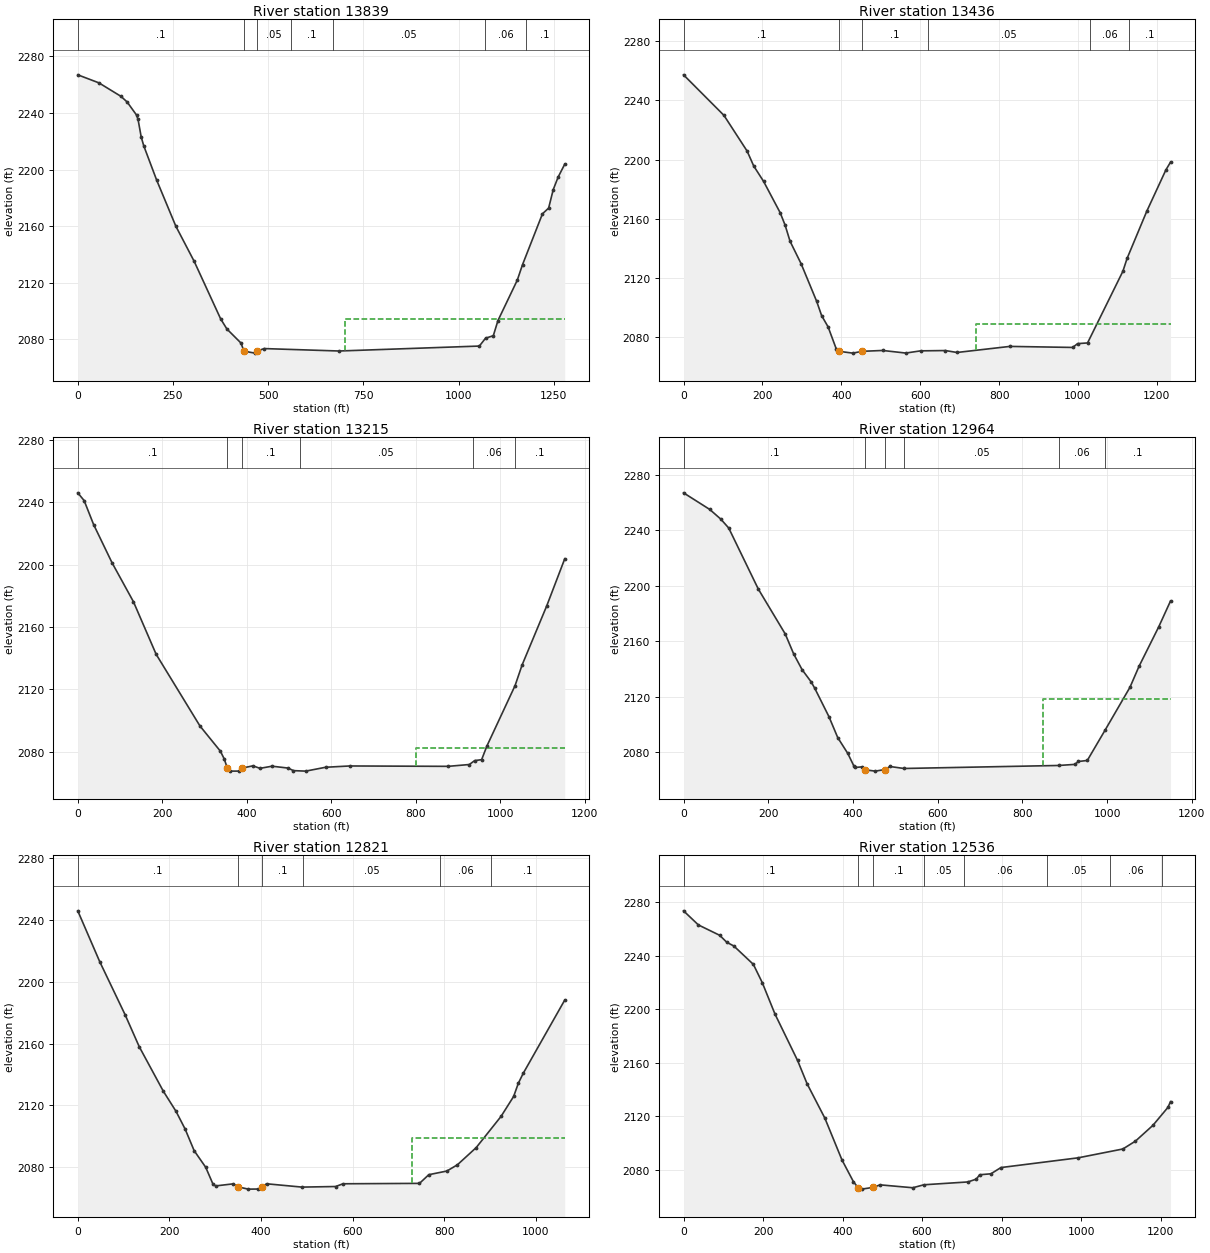
Type RM Length L Ch R = 1 ,13839   ,404.6,402.9,400.6
XS GIS Cut Line= 3
2184850.92184906399502.1559448542183789.58102373399730.192062141
2183598.17218435399754.567502174
#Sta/Elev= 30
       0 2267.01    55.4 2261.34   113.3  2251.8   129.5 2247.83   154.2 2238.59
   158.3 2235.42   166.5 2223.11   173.2 2216.83   206.9 2192.68   257.4 2159.97
   305.6 2135.08   375.1 2094.37   391.5  2087.2   428.3 2077.31   436.5  2071.5
   465.1 2070.12   471.4 2071.66   489.5 2073.34   686.1 2071.62  1054.3 2075.12
  1070.6 2080.68    1091 2082.45  1103.1 2093.12  1153.9 2121.75  1167.6 2132.67
    1220  2168.7  1236.2 2172.73  1248.3 2185.82  1261.2  2194.7  1278.5  2203.8
#Mann= 7 ,-1,0
       0      .1       0   436.5    .045       0   471.4     .05       0
     560      .1       0     670     .05       0    1070     .06       0
 1175.56      .1       0
#XS Ineff= 2 , 0
                          701.18         2094.21
Permanent Ineff=
       F       F
Bank Sta=436.5,471.4
XS Rating Curve= 0 ,0
Exp/Cntr=0.3,0.1

Type RM Length L Ch R = 1 ,13436   ,219.7,221.1,220
XS GIS Cut Line= 3
2184690.04264877399088.4428505072183687.72801939399400.867348081
2183504.64623514399425.262452826
#Sta/Elev= 30
       0 2257.31   102.5 2229.92   161.2 2205.81   177.9 2195.77   203.1 2185.28
     245 2164.19   257.5 2155.81   270.1 2144.89   298.2 2129.66   337.5 2104.36
   350.2 2094.62   366.5 2087.08   387.4 2072.05     395 2070.52   429.3 2069.34
   452.5 2070.55   504.7 2071.14   563.4 2069.39   601.1 2070.88   663.9 2071.08
   693.3 2069.78   827.3 2073.88   986.6 2073.18   999.1 2075.76  1024.3 2076.22
  1113.9 2124.64  1124.5  2133.3  1174.5 2165.22  1222.9 2193.09  1234.6 2198.32
#Mann= 6 ,-1,0
       0      .1       0     395    .045       0   452.5      .1       0
     620     .05       0    1030     .06       0 1129.88      .1       0
#XS Ineff= 2 , 0
                           742.2         2088.76
Permanent Ineff=
       F       F
Bank Sta=395,452.5
XS Rating Curve= 0 ,0
Exp/Cntr=0.3,0.1

Type RM Length L Ch R = 1 ,13215   ,259.6,250.8,243
XS GIS Cut Line= 4
2184573.62081751398837.5110686842184282.36039249398985.765248987
2184199.70540701399017.2528625032183491.23410291399223.234334251
#Sta/Elev= 30
       0 2246.04    15.1 2241.07    37.5 2225.71    81.1 2201.22   131.8 2176.21
   185.6 2142.47   289.3  2096.5   337.7 2080.34   346.7 2075.41  354.01 2069.63
   359.3 2067.53   380.8 2067.55     3902069.509   414.8 2070.93   431.4 2069.32
     460 2070.69   498.1 2069.49   510.6 2067.85   539.8 2067.53   586.9 2070.01
   643.7 2070.84   877.2  2070.6   927.2 2071.77   939.7 2074.26   956.3 2074.89
   968.8 2083.64  1035.5 2122.41  1052.1  2135.6  1110.4 2173.49  1153.1 2203.74
#Mann= 6 ,-1,0
       0      .1       0  354.01    .045       0     390      .1       0
  525.27     .05       0  935.27     .06       0 1035.27      .1       0
#XS Ineff= 2 , 0
                          799.77         2082.31
Permanent Ineff=
       F       F
Bank Sta=354.01,390
XS Rating Curve= 0 ,0
Exp/Cntr(USF)=0,0
Exp/Cntr=0.3,0.1

Type RM Length L Ch R = 1 ,12964   ,136.9,143.5,149.3
XS GIS Cut Line= 3
     2184451.778      398502.4722184040.80697291398845.560244107
2183457.77263613399039.918515592
#Sta/Elev= 30
       0 2266.92      62 2254.92    88.1 2247.93   106.7 2241.54   176.6  2197.5
   240.2 2165.11   260.1 2150.73   279.9 2139.41   301.7 2130.43   310.1 2125.81
   343.4 2105.46   364.2 2090.34   387.9 2078.95   402.1 2070.01   405.9 2068.86
   421.9 2069.29   428.7 2067.15   452.8  2066.2   475.9 2067.35   487.3 2069.54
   520.5 2068.11     886 2070.28   923.9 2071.06   932.4 2073.15   953.4 2073.89
   995.6 2095.85  1054.2 2126.69  1075.7 2141.88  1122.1 2170.27  1149.9 2188.89
#Mann= 6 ,-1,0
       0      .1       0   428.7    .045       0   475.9      .1       0
   520.5     .05       0     886     .06       0   995.6      .1       0
#XS Ineff= 2 , 0
                          849.77         2118.14
Permanent Ineff=
       F       F
Bank Sta=428.7,475.9
XS Rating Curve= 0 ,0
Exp/Cntr=0.3,0.1

Type RM Length L Ch R = 1 ,12821   ,276.5,284.4,282.4
XS GIS Cut Line= 4
2184337.46371615398495.0832717022183991.09996747 398697.12879176
2183597.50479853398770.5998899642183392.83531068398933.285893128
#Sta/Elev= 30
       0 2245.92    47.8 2213.11   103.4 2178.66   134.1 2158.05   186.7 2129.24
   214.5 2116.18   234.4 2104.68     254 2090.77   279.3 2079.98   294.9 2069.25
   300.8 2067.95   338.8 2069.28   350.5  2067.3     372 2065.88   394.4 2065.94
     4022067.356   412.1 2069.34   489.4 2067.19   562.7 2067.57   578.9 2069.34
   745.8  2069.6   766.1 2075.22   805.5 2077.58   828.6 2081.64   869.5 2092.73
   923.7  2112.9   951.3 2125.85   961.5 2134.36   972.1 2140.75  1062.8 2188.19
#Mann= 6 ,-1,0
       0      .1       0   350.5    .045       0     402      .1       0
  490.99     .05       0  790.99     .06       0  901.38      .1       0
#XS Ineff= 2 , 0
                          729.95         2098.99
Permanent Ineff=
       F       F
Bank Sta=350.5,402
XS Rating Curve= 0 ,0
Exp/Cntr(USF)=0,0
Exp/Cntr=0.3,0.1

Type RM Length L Ch R = 1 ,12536   ,497.9,468.3,434.9
BEGIN DESCRIPTION:
structure xs 4
END DESCRIPTION:
XS GIS Cut Line= 4
2184361.73058756398210.5652397042183917.62886927398429.484076877
2183659.16804166398441.2919319462183295.75125256398741.297773673
#Sta/Elev= 30
       0 2273.53    37.4 2262.98    90.9 2255.24   108.8 2250.02   126.6 2247.22
   175.7 2233.49     198 2219.91   230.1 2196.33   286.9 2161.65   310.8 2144.26
   355.6 2118.48   398.6 2087.26   427.3 2071.08   438.8 2066.62   448.2 2065.44
  477.83 2066.78   494.4 2068.64   576.7 2066.47   604.7 2068.69   715.2 2070.81
   736.8 2072.95   744.8 2076.18   773.3  2076.9   798.5 2081.57   992.4 2088.83
  1105.3 2095.46    1137 2101.36  1180.9 2113.15  1218.6 2126.56  1225.1 2130.89
#Mann= 8 ,-1,0
       0      .1       0   438.8    .045       0  477.83      .1       0
  605.13     .05       0  705.13     .06       0  913.86     .05       0
 1073.86     .06       0 1203.86      .1       0
Bank Sta=438.8,477.83
XS Rating Curve= 0 ,0
Exp/Cntr=0.5,0.3