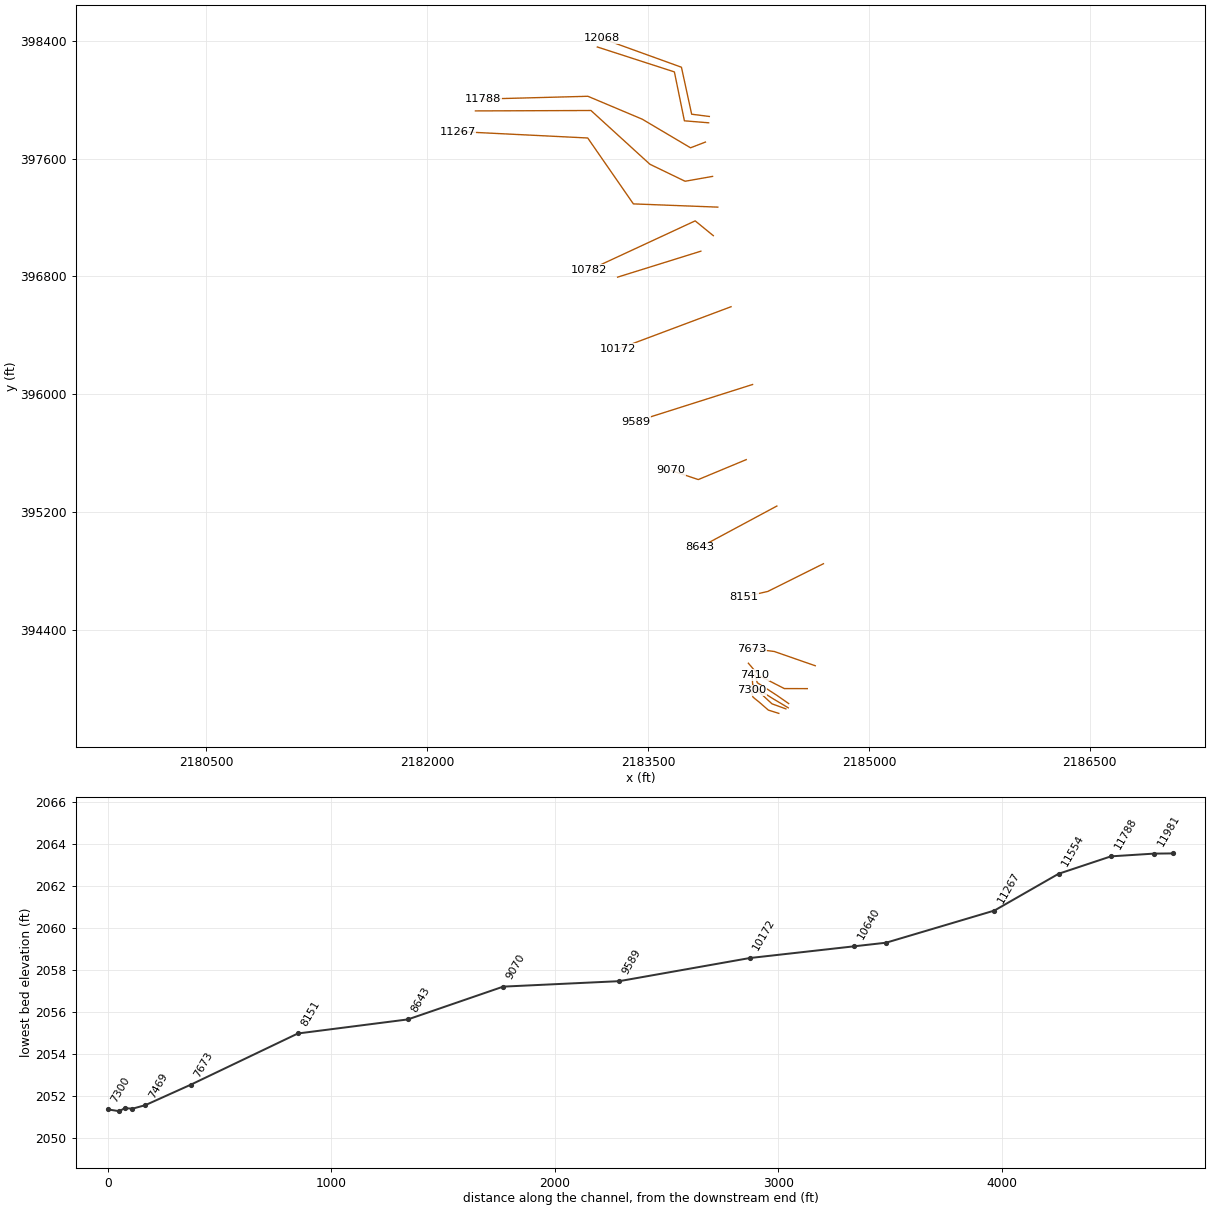
HEC-RAS study LCSTCK.prj: LCSTCK

--- LCSTCK.g01 (geometry) --- (continued)

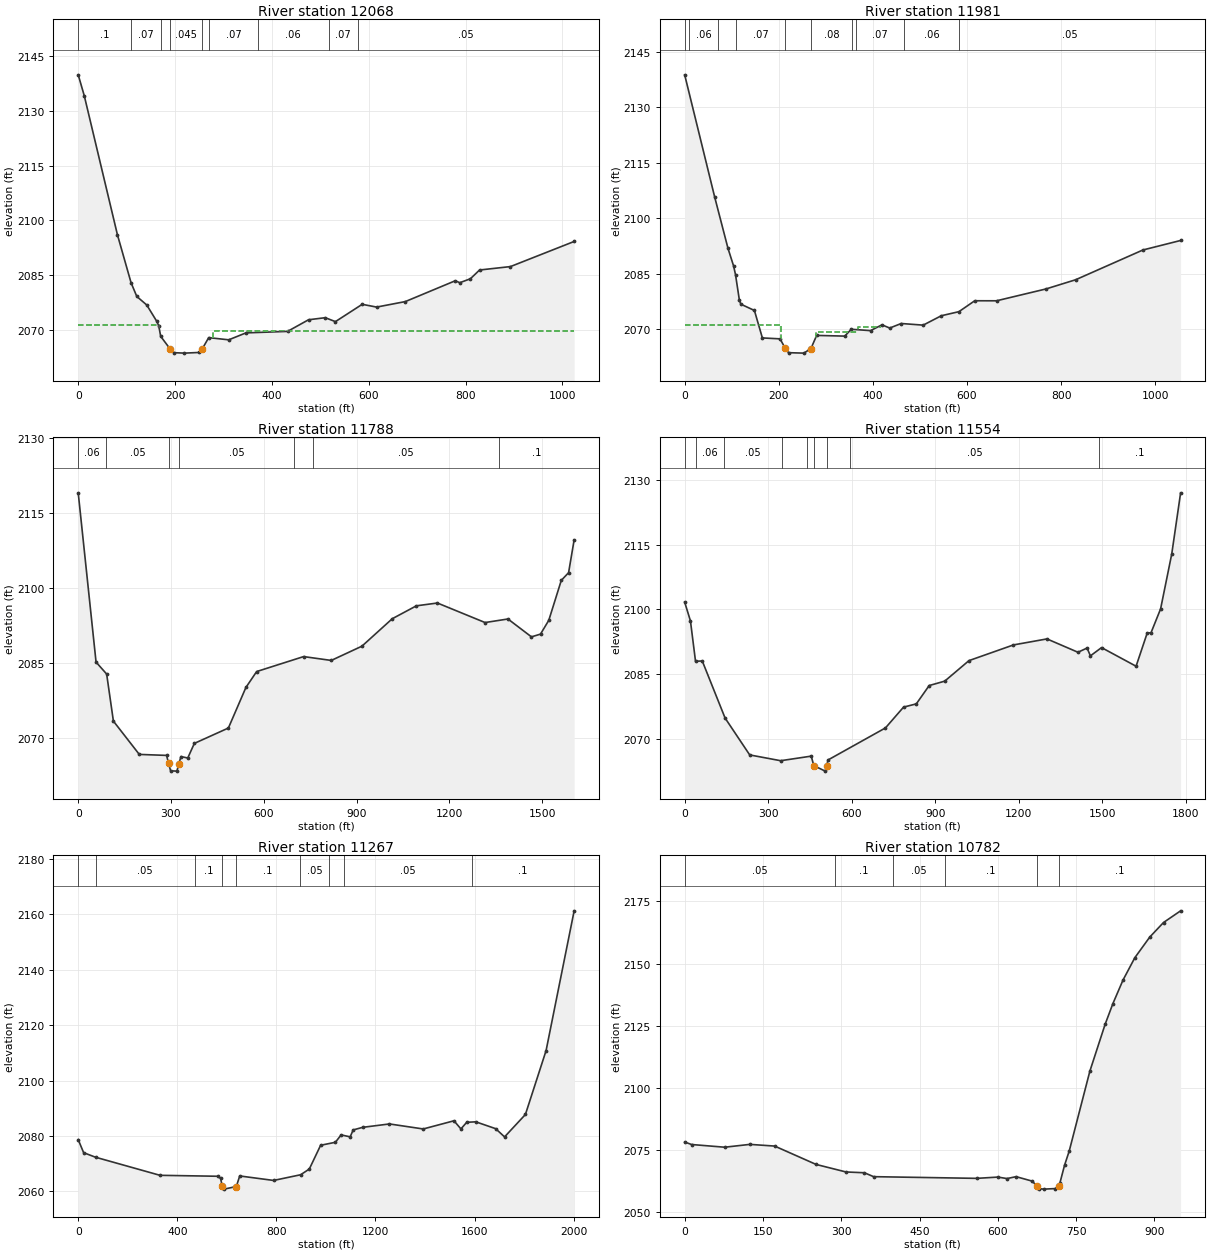
Type RM Length L Ch R = 1 ,12068   ,78.8,87.2,86
BEGIN DESCRIPTION:
structure xs 3; 23.6 ft between structure & xs
END DESCRIPTION:
XS GIS Cut Line= 4
2183916.54863486397885.6286257112183796.56039815397900.886686507
2183727.18390179398219.7751434912183184.34324601398415.733317439
#Sta/Elev= 30
       0  2139.9    12.5 2134.17      81 2096.03   109.2 2082.86     121 2079.11
   141.6 2076.76   162.2 2072.29   166.3 2071.07   170.4 2068.16  189.912064.686
     198 2063.68   219.5 2063.56   249.3 2063.74     256 2064.67   269.5 2067.81
   310.9 2067.21   346.4 2069.11   432.4 2069.52   475.7 2072.71   510.3 2073.28
   531.3  2072.2   586.6 2076.95   616.4 2076.19   675.7  2077.7   778.8 2083.41
   788.2 2082.88   810.1 2083.96     829 2086.36   892.8  2087.3  1024.4 2094.19
#Mann= 9 ,-1,0
       0      .1       0     110     .07       0  170.95     .08       0
  189.91    .045       0     256     .08       0  270.95     .07       0
  370.95     .06       0   517.3     .07       0   577.3     .05       0
#XS Ineff= 2 , 0
           167.2 2071.15   278.1         2069.71
Permanent Ineff=
       F       F
Bank Sta=189.91,256
XS Rating Curve= 0 ,0
Exp/Cntr(USF)=0,0
Exp/Cntr=0.5,0.3

Type RM Length L Ch R = 1 ,11981   ,168.6,192.3,219.7
BEGIN DESCRIPTION:
structure xs 2; 33 ft between structure & xs
END DESCRIPTION:
XS GIS Cut Line= 4
 2183911.8493699397842.6905004782183747.33505043397856.062127386
2183679.32879477398187.9443110882183155.96224323398357.125591702
#Sta/Elev= 30
       0  2138.8    63.9 2105.68      92  2091.9     104 2087.09     108 2084.78
   116.1 2078.01   119.2  2076.8   148.2 2075.08   165.1 2067.66   202.6 2067.41
  213.762064.861   220.7 2063.67   253.4 2063.55   268.3  2064.8   280.5 2068.34
   340.2 2068.15     354    2070   394.9 2069.63   419.3  2071.2   435.7 2070.33
   460.1 2071.56   506.8 2071.12   545.4 2073.66   582.8 2074.76   616.4 2077.71
   662.7  2077.7   767.7  2080.9   830.8 2083.39   973.8 2091.44  1053.9 2094.01
#Mann= 10 ,-1,0
       0      .1       0      10     .06       0      70      .1       0
     110     .07       0  213.76    .045       0   268.3     .08       0
  355.06     .05       0  365.06     .07       0  465.06     .06       0
  583.83     .05       0
#XS Ineff= 3 ,-1
       0     205 2071.15     278  367.83 2069.21  367.83  416.55 2070.56
Permanent Ineff=
       F       F       F
Bank Sta=213.76,268.3
XS Rating Curve= 0 ,0
Exp/Cntr(USF)=0,0
Exp/Cntr=0.5,0.3

Type RM Length L Ch R = 1 ,11788   ,238,234.4,226.7
BEGIN DESCRIPTION:
structure xs 1
END DESCRIPTION:
XS GIS Cut Line= 5
2183889.99825816397711.942396879 2183788.9763424397672.994188393
2183461.08961566397867.088964366 2183092.0860736398022.561473342
2182378.18821534398003.596182619
#Sta/Elev= 30
       0 2119.01    57.7  2085.2      92 2082.81   113.8 2073.41   197.5 2066.76
   285.8 2066.56  292.272064.968   298.8 2063.48   319.2 2063.42  325.622064.927
   332.3 2066.33   354.3 2066.04   375.6 2068.96   485.7 2072.03   542.4 2080.14
   577.1 2083.31     729  2086.3   818.4 2085.53   917.6 2088.38  1015.6 2093.86
  1093.7 2096.44  1161.7    2097  1315.8  2093.1  1389.8 2093.81  1465.8 2090.24
  1495.1 2090.79  1521.9 2093.55  1562.3 2101.52  1585.9 2103.06  1603.9 2109.62
#Mann= 7 ,-1,0
       0     .06       0      90     .05       0  292.27    .045       0
  325.62     .05       0   699.3     .08       0   759.3     .05       0
 1359.72      .1       0
Bank Sta=292.27,325.62
XS Rating Curve= 0 ,0
Exp/Cntr(USF)=0,0
Exp/Cntr=0.3,0.1

Type RM Length L Ch R = 1 ,11554   ,299.3,287.2,281.4
XS GIS Cut Line= 5
2183938.43925565397478.9434904042183751.91305203 397446.02710153
2183513.26923269 397561.234462592183112.78650139397926.057772615
2182328.27923321397923.314740209
#Sta/Elev= 30
       0 2101.68    20.7 2097.35    38.9 2088.02    63.2 2088.07     145 2074.88
   233.5 2066.34   344.6    2065   454.4 2066.06   463.6 2063.87   504.6 2062.59
     510 2063.84   514.6 2065.17     721 2072.59   785.9  2077.4   831.7 2078.15
   877.9 2082.39   933.7 2083.41  1020.8 2088.16  1180.5 2091.79  1300.8 2093.18
  1412.2 2090.09  1444.8 2091.07  1456.8 2089.26  1496.8 2091.17  1620.8 2086.86
  1660.8 2094.56  1674.3 2094.59  1708.8 2100.12  1748.8 2112.82  1780.7 2126.98
#Mann= 9 ,-1,0
       0      .1       0      40     .06       0     140     .05       0
  349.41      .1       0  439.41     .05       0   463.6    .045       0
     510      .1       0  594.41     .05       0 1486.15      .1       0
Bank Sta=463.6,510
XS Rating Curve= 0 ,0
Exp/Cntr(USF)=0,0
Exp/Cntr=0.3,0.1

Type RM Length L Ch R = 1 ,11267   ,435.2,484.6,520.2
XS GIS Cut Line= 4
2183974.09867694397270.4730275332183400.80490404397292.417286783
2183090.84224214397739.5315689932182207.58580734397783.420087493
#Sta/Elev= 30
       0 2078.68    21.9 2073.98      70 2072.34   330.2 2065.82   562.3 2065.48
   574.7 2064.72   581.8 2061.83   589.1 2060.84  638.292061.786     652 2065.59
   788.8 2063.97   897.8 2066.02   932.9 2068.08   978.6 2076.65  1038.2 2077.73
  1061.4 2080.39  1097.9 2079.69    1110 2082.18  1148.3 2083.12  1256.6 2084.34
  1392.8 2082.53  1516.9 2085.48    1545 2082.55  1568.3 2084.93    1605 2085.11
  1685.1 2082.64  1721.2 2079.67  1805.3 2087.75  1888.8 2110.79  2002.1 2161.18
#Mann= 9 ,-1,0
       0     .06       0      70     .05       0     470      .1       0
   581.8    .045       0  638.29      .1       0  893.71     .05       0
 1013.71     .06       0 1073.71     .05       0 1587.76      .1       0
Bank Sta=581.8,638.29
XS Rating Curve= 0 ,0
Exp/Cntr(USF)=0,0
Exp/Cntr=0.3,0.1

Type RM Length L Ch R = 1 ,10782   ,145,141.8,140.4
XS GIS Cut Line= 3
2183943.61298548397076.8520688982183820.48886219397177.209925722
2183102.43004698396844.302796681
#Sta/Elev= 30
       0 2078.26    13.2 2077.25    76.7 2076.16   124.9  2077.3   172.4 2076.62
   251.8 2069.24   309.1 2066.21   344.4 2065.89     362 2064.32   559.7 2063.64
   600.1 2064.15   617.7 2063.56   635.1 2064.32   666.2 2062.51674.3982 2060.57
   679.4 2059.48   688.3 2059.31   710.3 2059.53716.48722060.679   719.1 2061.85
   727.9 2068.92   736.8 2074.59   776.4 2106.74   805.6 2125.56   820.5 2133.88
   839.9 2143.36   862.6 2152.36   891.1 2160.63   917.5  2166.5   950.3  2171.2
#Mann= 6 ,-1,0
       0     .05       0  288.84      .1       0  398.84     .05       0
  498.84      .1       0674.3982    .045       0716.4872      .1       0
Bank Sta=674.3982,716.4872
XS Rating Curve= 0 ,0
Exp/Cntr(USF)=0,0
Exp/Cntr=0.3,0.1

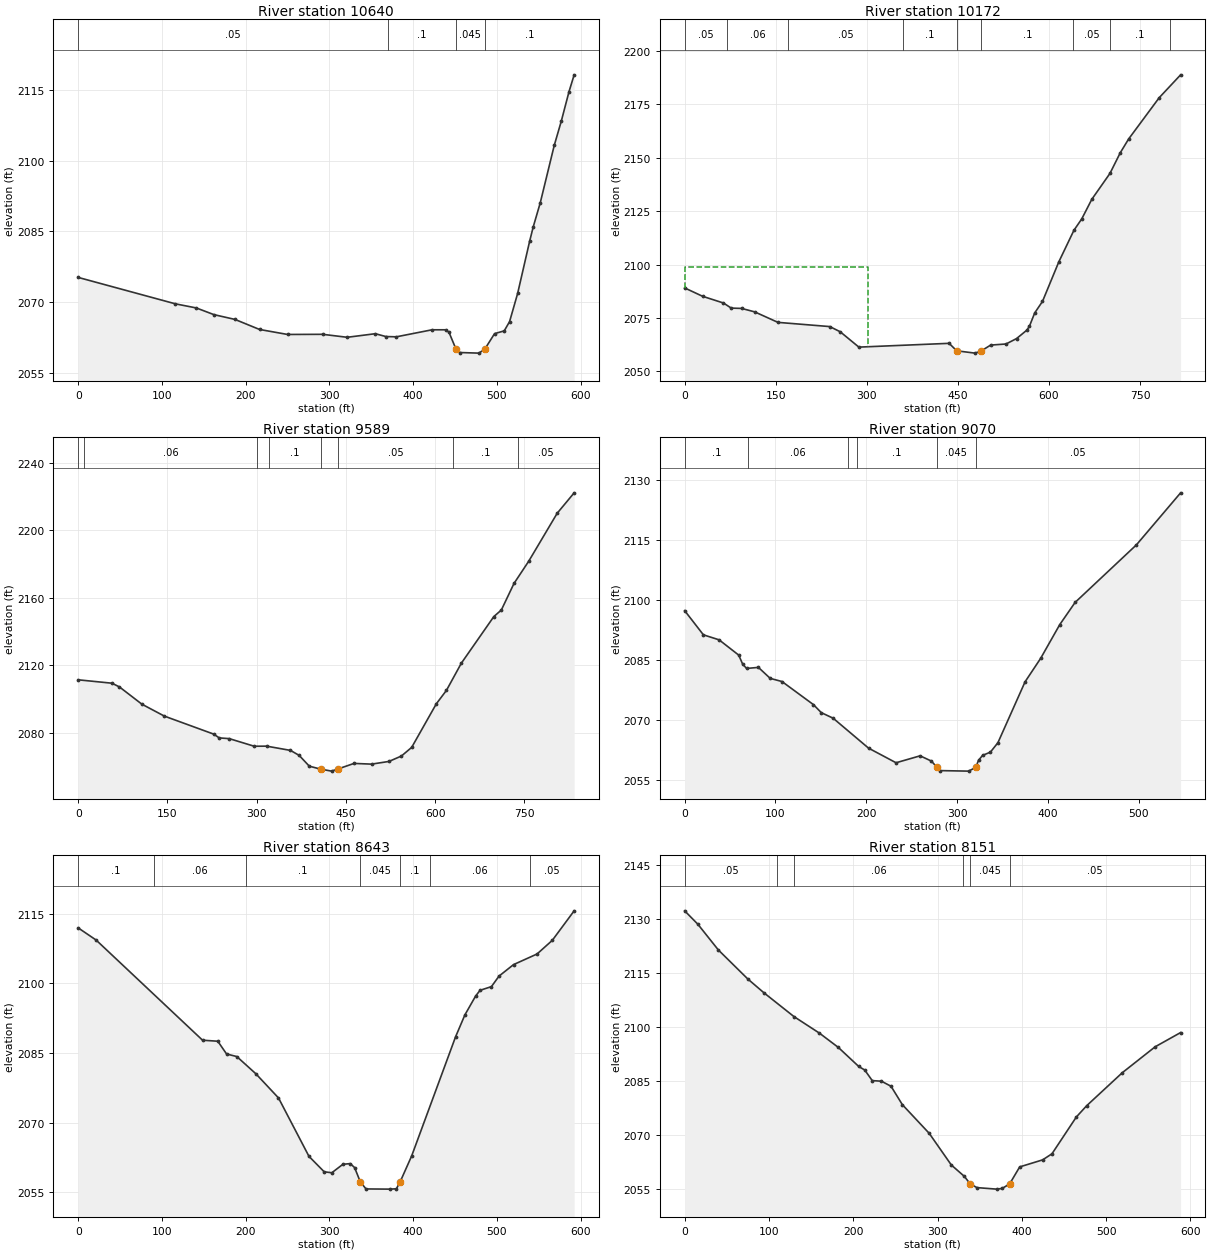
Type RM Length L Ch R = 1 ,10640   ,464.4,468.4,466.3
XS GIS Cut Line= 2
2183858.88879444 396971.43796172 2183293.5059123396795.349190994
#Sta/Elev= 30
       0  2075.2     116  2069.6   141.1 2068.72     162 2067.31   187.2 2066.29
   216.5 2064.16     250  2063.1   291.9 2063.13   321.2  2062.5   354.8 2063.26
   367.3 2062.66   379.9  2062.6   422.5 2064.09   438.6 2064.09   442.7 2063.58
   451.1 2059.99   455.3 2059.27   478.4 2059.14  485.412059.965   497.2 2063.28
   508.7 2063.86   515.1 2065.83   524.7 2071.79   539.1 2082.92   543.3  2085.9
   551.7 2091.01   568.4 2103.19   576.8 2108.32     586 2114.57   592.2 2118.18
#Mann= 4 ,-1,0
       0     .05       0     370      .1       0   451.1    .045       0
  485.41      .1       0
Bank Sta=451.1,485.41
XS Rating Curve= 0 ,0
Exp/Cntr(USF)=0,0
Exp/Cntr=0.3,0.1

Type RM Length L Ch R = 1 ,10172   ,577.7,583.5,576.4
XS GIS Cut Line= 2
2184064.01263722  396594.60982682183299.16299071396308.070184662
#Sta/Elev= 30
       0 2089.06    29.7 2085.13    63.9 2082.01    76.7 2079.63    93.8 2079.48
   115.2 2077.88   153.6 2072.96     239 2070.99   256.1 2068.58   286.9 2061.39
   435.5 2063.16   448.1 2059.66   478.2 2058.58   488.8 2059.67   503.9 2062.34
   529.2 2062.85   546.6 2065.38   563.7 2069.36   567.9 2071.23   576.5 2077.38
   589.3 2082.75   616.2 2101.25   641.1 2116.02     654 2121.35   670.5 2130.48
   700.4 2142.59   717.4 2152.25   731.2  2158.7   781.5 2177.99   816.8 2188.69
#Mann= 9 ,-1,0
       0     .05       0      70     .06       0     170     .05       0
     360      .1       0   448.1    .045       0   488.8      .1       0
     640     .05       0     700      .1       0     800     .05       0
#XS Ineff= 2 , 0
          302.61 2098.64
Permanent Ineff=
       F       F
Bank Sta=448.1,488.8
XS Rating Curve= 0 ,0
Exp/Cntr=0.3,0.1

Type RM Length L Ch R = 1 ,9589    ,512.9,519,519.1
XS GIS Cut Line= 2
2184210.19901468396066.9257373842183415.48507717 395815.01475812
#Sta/Elev= 30
       0 2111.48    56.7 2109.48    69.3 2107.28     107 2097.08   144.8 2090.02
   227.7 2079.38   237.1 2077.13   253.9  2076.7   295.9  2072.2   316.8 2072.25
   356.8 2069.74   371.4  2066.8   388.5  2060.4   407.6 2058.66   425.9 2057.48
   436.6 2058.75   463.7 2062.04   493.1 2061.62   522.4 2063.21   543.4 2066.43
   560.6 2071.53     602 2097.29     619 2105.23   644.1 2121.34   698.7 2148.89
   711.3 2152.76   732.6 2168.49   757.4 2181.67   805.2    2210   833.7 2222.07
#Mann= 8 ,-1,0
       0     .05       0      10     .06       0     300     .05       0
     320      .1       0   407.6    .045       0   436.6     .05       0
     630      .1       0     740     .05       0
Bank Sta=407.6,436.6
XS Rating Curve= 0 ,0
Exp/Cntr(USF)=0,0
Exp/Cntr=0.3,0.1

Type RM Length L Ch R = 1 ,9070    ,417.5,426.5,421.1
XS GIS Cut Line= 3
2184167.14856259395557.1365181952183841.56088507 395421.87900706
2183658.01009118395483.513000903
#Sta/Elev= 30
       0 2097.27    20.6 2091.24    37.9 2089.99    59.5 2086.18    63.9  2083.9
    68.2 2082.85    81.2 2083.11    94.2 2080.37   107.2 2079.58   141.8 2073.82
   150.5 2071.81   163.5 2070.43   202.5 2062.96   232.8 2059.31   259.3 2061.04
   271.8 2059.72   277.7 2058.19   281.4 2057.35   312.7 2057.22   320.5 2058.14
   323.7 2059.95   328.1 2061.15   336.7 2061.96     345 2064.32   374.9 2079.52
     392 2085.35   413.1 2093.79     430 2099.33   497.5 2113.69   546.2 2126.68
#Mann= 6 ,-1,0
       0      .1       0      70     .06       0     180     .05       0
     190      .1       0   277.7    .045       0   320.5     .05       0
Bank Sta=277.7,320.5
XS Rating Curve= 0 ,0
Exp/Cntr(USF)=0,0
Exp/Cntr=0.3,0.1

Type RM Length L Ch R = 1 ,8643    ,495,492.3,493.3
XS GIS Cut Line= 2
2184375.05535959395242.2647120842183853.10888422394962.188471107
#Sta/Elev= 30
       0 2111.95    21.4 2109.33   148.5 2087.75   166.7 2087.53   177.2 2084.78
   189.4 2084.23   212.1 2080.53   239.2 2075.31   275.6 2062.72   293.8 2059.39
   302.9 2059.19   316.1 2061.01   324.9 2061.16   330.1  2060.3   336.8 2057.27
   343.7  2055.7   372.2 2055.66     380 2055.73   384.6 2057.28   398.2 2062.79
   450.7 2088.49   461.8  2093.2   474.6 2097.26   479.9  2098.5   493.5  2099.3
   502.6 2101.57   519.9 2104.04     548 2106.33   566.2 2109.27   592.3 2115.63
#Mann= 7 ,-1,0
       0      .1       0      90     .06       0     200      .1       0
   336.8    .045       0   384.6      .1       0     420     .06       0
     540     .05       0
Bank Sta=336.8,384.6
XS Rating Curve= 0 ,0
Exp/Cntr(USF)=0,0
Exp/Cntr=0.3,0.1

Type RM Length L Ch R = 1 ,8151    ,497.9,477.6,457.2
XS GIS Cut Line= 3
2184691.33300078394850.9682945672184313.72422378394662.904728095
2184151.45468369394625.723571917
#Sta/Elev= 30
       0 2132.24    15.6 2128.53    39.9 2121.39      75  2113.3    93.7 2109.55
   129.6 2102.89   159.9 2098.28   182.3 2094.32   206.5 2089.03   213.6 2088.05
   222.5 2085.11   233.4 2084.95   244.8 2083.54   258.2 2078.44   290.1 2070.47
   316.3 2061.69   331.8 2058.52   338.7 2056.44   346.7 2055.41     370 2054.99
   376.6 2055.18   385.5 2056.44   397.4 2061.16   424.6 2063.11   435.7  2064.8
   464.6 2075.01   476.8 2078.13   519.1  2087.3   558.1  2094.5   588.3 2098.45
#Mann= 6 ,-1,0
       0     .05       0     110      .1       0     130     .06       0
     330      .1       0   338.7    .045       0   385.5     .05       0
Bank Sta=338.7,385.5
XS Rating Curve= 0 ,0
Exp/Cntr=0.3,0.1

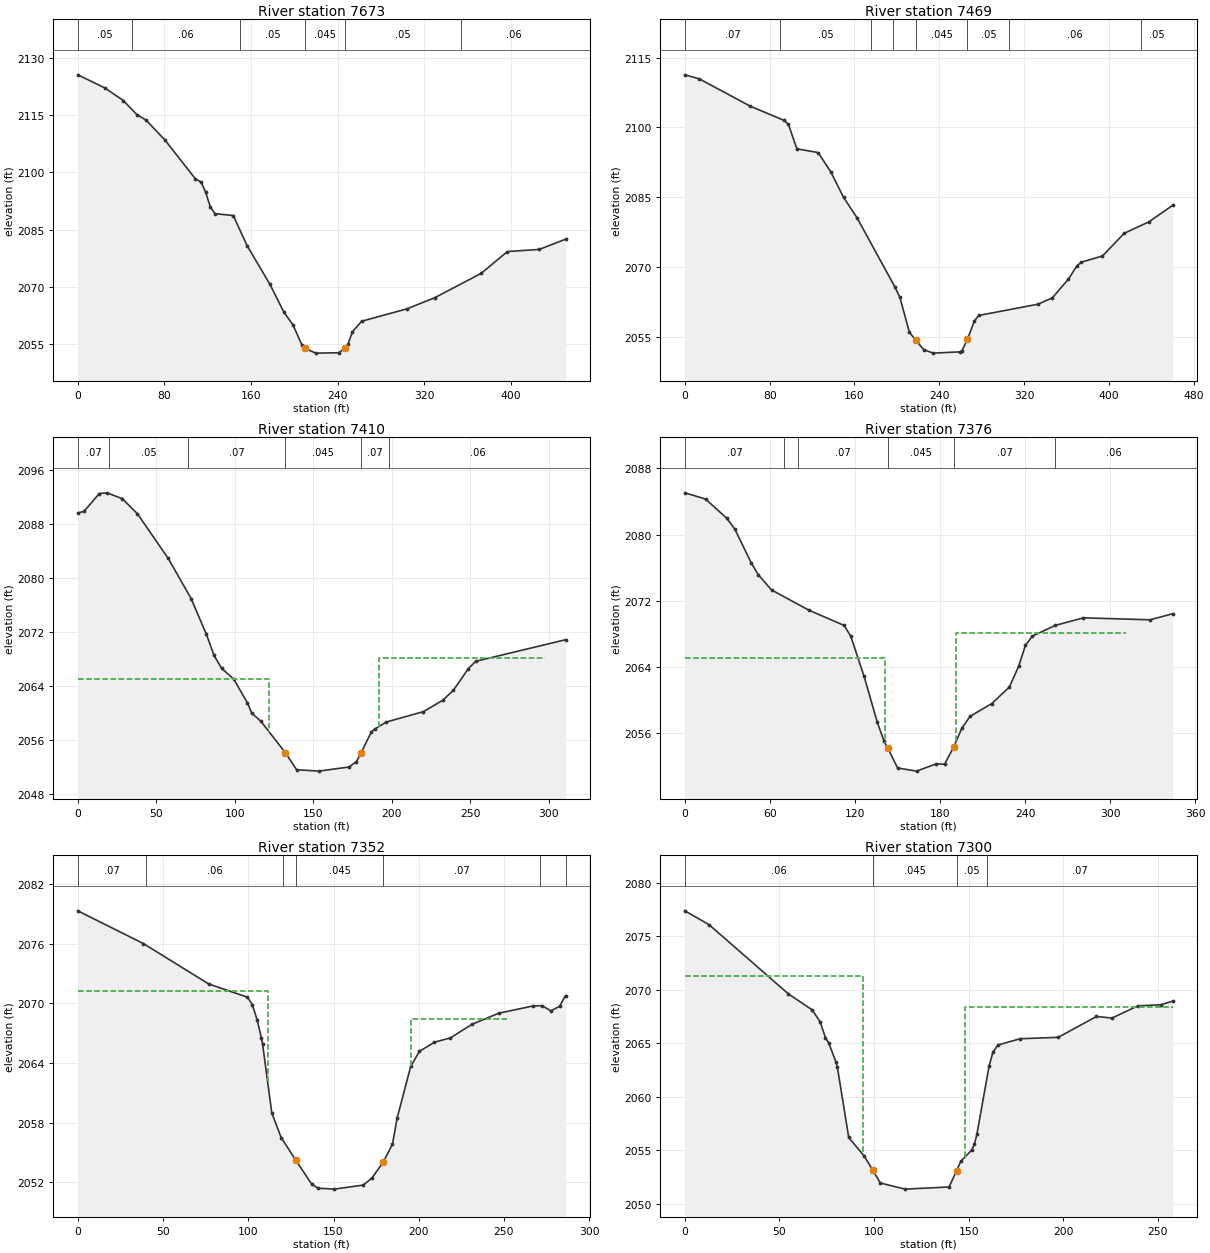
Type RM Length L Ch R = 1 ,7673    ,207.9,204.5,200
XS GIS Cut Line= 3
2184635.80103083394158.6160273562184357.83299713394255.313805759
2184202.87220755 394274.98916073
#Sta/Elev= 30
       0 2125.59      25 2122.15      42 2118.85    54.7 2115.12    63.1  2113.7
    80.3 2108.54   108.6  2098.3     114  2097.4     118 2094.83   122.4 2090.96
   126.7 2089.16   143.6 2088.67   156.3  2080.8   177.5  2070.6   190.2 2063.39
   198.7 2059.99   207.1 2054.65   209.5 2053.84   219.8 2052.56     241 2052.66
   246.8 2053.85   249.5 2054.87   253.7 2058.19   262.2 2060.93     304 2064.18
   329.7  2067.1   372.6  2073.5   396.8 2079.21   426.3 2079.78   450.5 2082.45
#Mann= 6 ,-1,0
       0     .05       0      50     .06       0     150     .05       0
   209.5    .045       0   246.8     .05       0  354.31     .06       0
Bank Sta=209.5,246.8
XS Rating Curve= 0 ,0
Exp/Cntr(USF)=0,0
Exp/Cntr=0.3,0.1

Type RM Length L Ch R = 1 ,7469    ,61.1,58.2,55.5
BEGIN DESCRIPTION:
structure xs 4
END DESCRIPTION:
XS GIS Cut Line= 4
2184581.86180696394003.4272497682184425.80634744394003.790504337
2184252.84669636394092.4215693182184181.61600522394175.811779235
#Sta/Elev= 30
       0 2111.29    13.7 2110.42    61.7 2104.57    93.7 2101.51    97.7 2100.68
   105.7 2095.41   125.7 2094.62   137.7 2090.48   149.7 2085.02   162.4 2080.64
   198.3 2065.72   202.9 2063.54   211.8 2056.06   217.7 2054.41   225.3 2052.33
   234.3 2051.58   259.3 2051.85   261.3 2052.06  266.622054.522   273.1 2058.44
   277.2 2059.66   333.2 2062.08   346.7 2063.45   361.9 2067.48   369.9 2070.32
   374.1 2071.09     394 2072.43   414.5 2077.29   437.7 2079.74   460.1 2083.27
#Mann= 8 ,-1,0
       0     .07       0      90     .05       0  176.06      .1       0
  196.06     .05       0   217.7    .045       0  266.62     .05       0
  306.06     .06       0   430.4     .05       0
Bank Sta=217.7,266.62
XS Rating Curve= 0 ,0
Exp/Cntr(USF)=0,0
Exp/Cntr=0.5,0.3

Type RM Length L Ch R = 1 ,7410    ,33.8,34.2,34.1
BEGIN DESCRIPTION:
structure xs 3; 11.4 ft between structure & xs
END DESCRIPTION:
XS GIS Cut Line= 4
2184455.40458074393902.0861319622184374.52090114393958.349607642
2184242.00339213394043.6047773332184226.58769049394095.971668611
#Sta/Elev= 30
       0 2089.59     3.9 2089.81    13.7 2092.45    18.6 2092.56    28.3  2091.7
      38 2089.46    57.5  2082.9    72.2 2076.92    81.9 2071.65    86.8 2068.51
    91.6 2066.62    99.4 2064.99   108.1 2061.48   110.8    2060   116.7 2058.76
  132.192054.147   139.4 2051.62   153.6 2051.41   172.7 2052.02   177.4 2052.78
   180.4 2054.08   186.9 2057.16   189.1 2057.62   196.4 2058.66   220.2 2060.21
   232.5 2061.89   239.3 2063.38   248.8 2066.57   253.5 2067.65   310.7 2070.84
#Mann= 6 ,-1,0
       0     .07       0      20     .05       0      70     .07       0
  132.19    .045       0   180.4     .07       0  198.53     .06       0
#XS Ineff= 2 ,-1
   191.8   297.4 2068.12       0     122 2065.05
Permanent Ineff=
       F       F
Bank Sta=132.19,180.4
XS Rating Curve= 0 ,0
Exp/Cntr(USF)=0,0
Exp/Cntr=0.5,0.3

Type RM Length L Ch R = 1 ,7376    ,30.1,23.9,18.4
BEGIN DESCRIPTION:
structure xs 2; 6.3 ft between structure & xs
END DESCRIPTION:
XS GIS Cut Line= 5
 2184452.7433218393873.2035463732184342.67486177393938.768367556
2184230.47681757394010.5968592572184211.26952681394029.151471357
2184206.69292758 394085.03268738
#Sta/Elev= 30
       0 2085.04    14.6 2084.29    29.6 2081.97    35.4 2080.62    46.8  2076.6
    51.9 2075.13    61.2 2073.31    87.9 2070.84   112.4 2069.03   117.1 2067.72
   126.4 2062.92   135.8 2057.33   140.6 2055.03   143.3 2054.18   150.1 2051.82
   163.5 2051.44   177.1  2052.3   183.3 2052.29   189.6 2054.32   195.4  2056.6
   201.2 2058.05   216.6  2059.6     229  2061.6   235.6 2064.14   240.3 2066.62
   245.1 2067.73   261.3 2069.03   281.2 2069.95   328.2 2069.71   344.1 2070.44
#Mann= 6 ,-1,0
       0     .07       0      70     .06       0      80     .07       0
   143.3    .045       0   189.6     .07       0  261.34     .06       0
#XS Ineff= 2 ,-1
   191.6   311.4 2068.12       0   141.3 2065.05
Permanent Ineff=
       F       F
Bank Sta=143.3,189.6
XS Rating Curve= 0 ,0
Exp/Cntr(USF)=0,0
Exp/Cntr=0.5,0.3

Type RM Length L Ch R = 1 ,7352    ,50.5,52.5,54.3
BEGIN DESCRIPTION:
structure xs 3; 16.3 ft between structure & xs
END DESCRIPTION:
XS GIS Cut Line= 4
2184436.41147292393866.0033117032184342.04127592 393900.23811529
 2184275.2481729393961.914462794 2184201.4581829394021.463410018
#Sta/Elev= 30
       0 2079.33    38.5 2076.03    76.8 2071.96    99.5 2070.63   102.4 2069.87
   105.2 2068.34   107.7 2066.52   108.4  2065.9   113.8 2058.96   119.3 2056.49
   127.9 2054.19   137.2  2051.8     141 2051.38   150.5 2051.29   167.5  2051.7
   172.5  2052.4   179.2 2054.01   184.6 2055.82   187.3 2058.42   195.3 2063.66
   200.4 2065.17   209.2 2066.09   218.6 2066.53   231.2 2067.89     247 2069.02
   267.2 2069.75   272.4 2069.77   277.5 2069.25   282.6 2069.71   286.1 2070.79
#Mann= 7 ,-1,0
       0     .07       0      40     .06       0  120.39     .07       0
   127.9    .045       0   179.2     .07       0   271.3     .06       0
  286.12     .05       0
#XS Ineff= 2 ,-1
       0   111.6  2071.3   195.5     252  2068.4
Permanent Ineff=
       F       F
Bank Sta=127.9,179.2
XS Rating Curve= 0 ,0
Exp/Cntr(USF)=0,0
Exp/Cntr=0.5,0.3

Type RM Length L Ch R = 1 ,7300    ,17,16.7,16.2
BEGIN DESCRIPTION:
structure xs 2; 14 ft between structure & xs
END DESCRIPTION:
XS GIS Cut Line= 6
2184388.41503412 393835.480985792184317.45006202 393857.60777865
 2184253.0866567393913.5003347272184213.68382496393945.269793044
2184206.72280869393963.646875986 2184205.0019618393991.429652735
#Sta/Elev= 30
       0 2077.36    12.8 2076.07    54.7 2069.61    67.3 2068.11    71.5 2066.99
    74.3 2065.52      76 2065.04    79.8 2063.27    80.6 2062.76    86.6  2056.2
    94.8 2054.46   99.162053.195   103.3 2051.95   116.4 2051.38   139.6 2051.58
  143.542053.086   145.8 2053.98   151.5 2055.01     153 2055.57   154.3 2056.49
   160.8  2062.9   162.8 2064.17   165.4 2064.83   177.1 2065.42   197.3 2065.55
   217.5  2067.5   225.7 2067.35   239.4 2068.49   251.4 2068.59   257.7 2068.92
#Mann= 4 ,-1,0
       0     .06       0   99.16    .045       0  143.54     .05       0
  159.58     .07       0
#XS Ineff= 2 , 0
              94  2071.3   148.2          2068.4
Permanent Ineff=
       F       F
Bank Sta=99.16,143.54
XS Rating Curve= 0 ,0
Exp/Cntr(USF)=0,0
Exp/Cntr=0.5,0.3