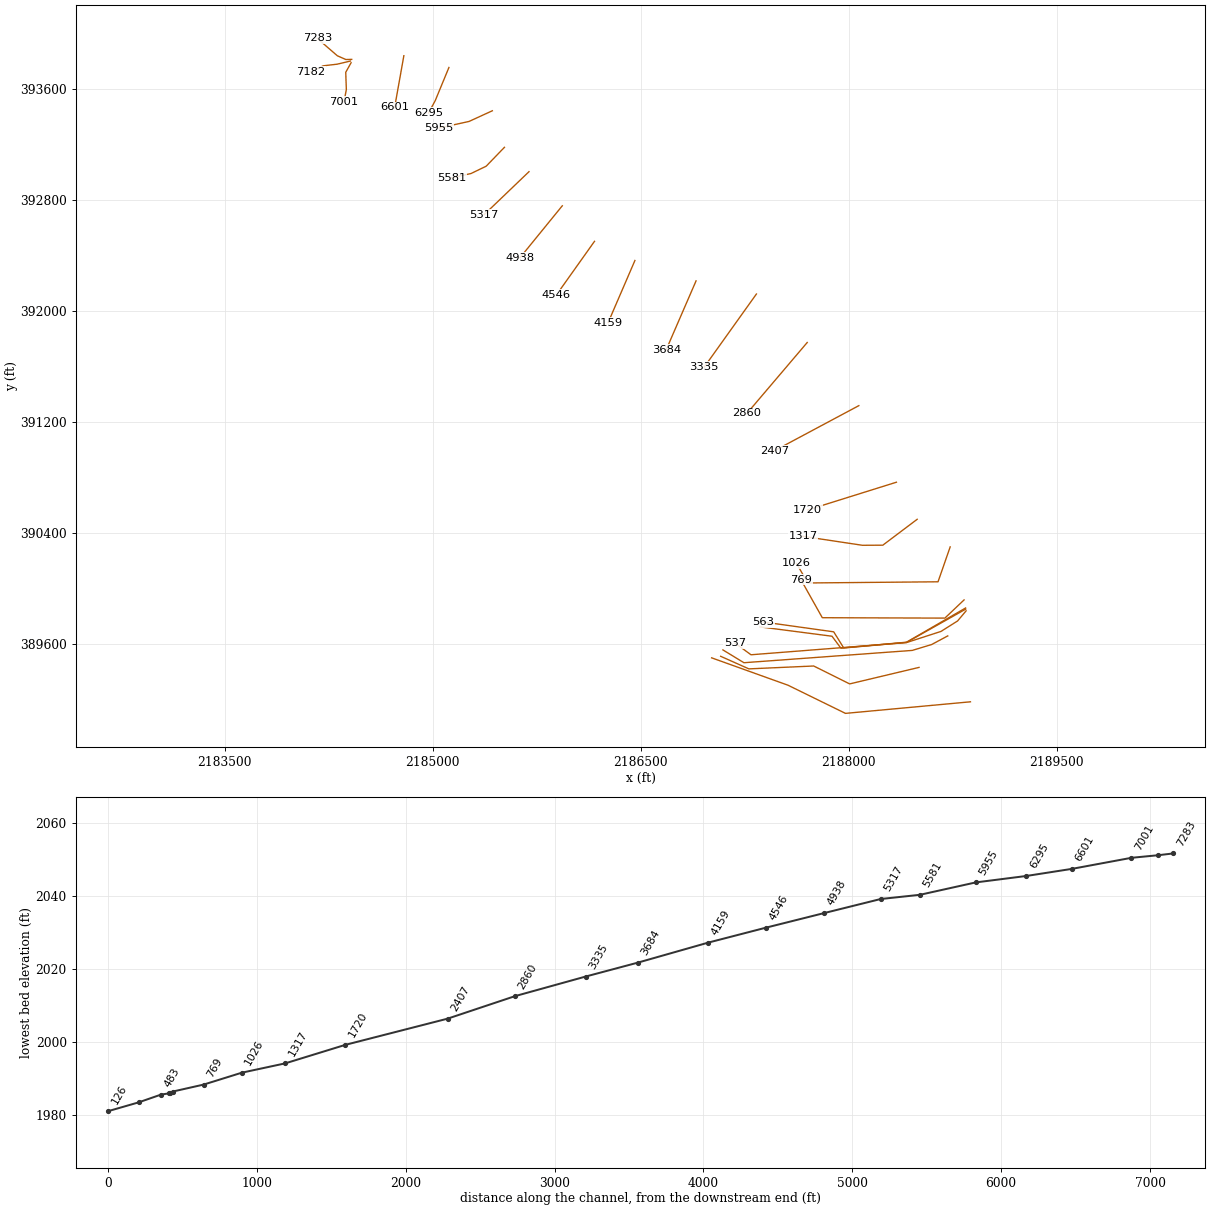
HEC-RAS study LCSTCK.prj: LCSTCK

--- LCSTCK.g01 (geometry) --- (continued)

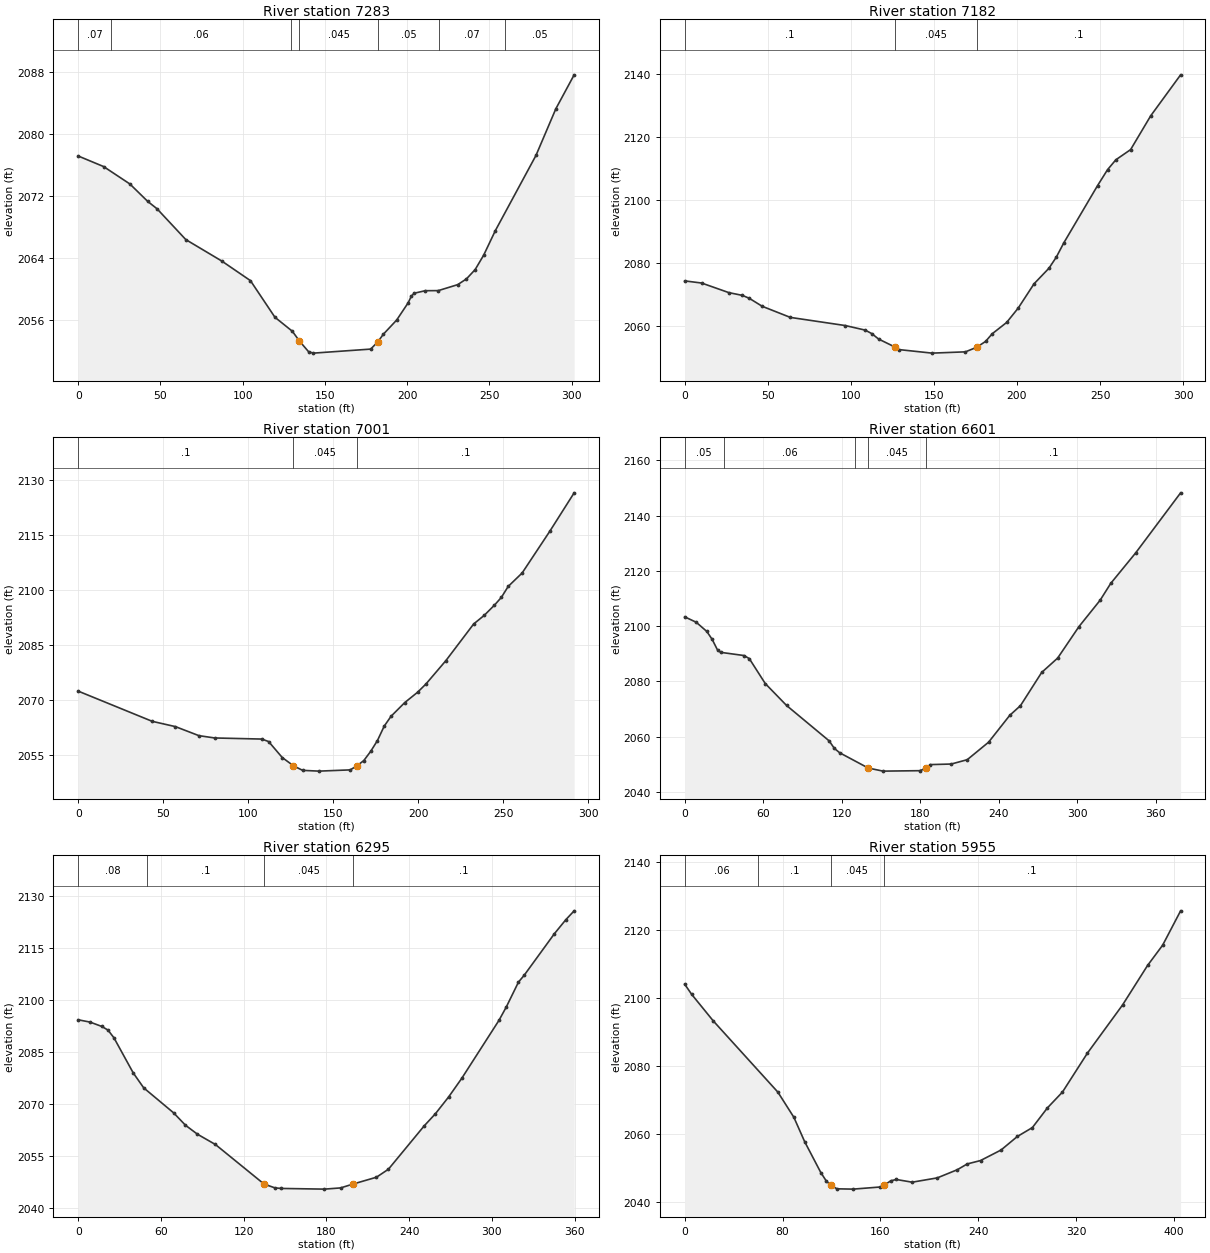
Type RM Length L Ch R = 1 ,7283    ,77.8,100.8,125.3
BEGIN DESCRIPTION:
structure xs 1
END DESCRIPTION:
XS GIS Cut Line= 4
2184415.57662666393815.5077598172184373.26692267393814.481433504
2184311.85560604393841.532612537 2184166.6230518393967.228482741
#Sta/Elev= 30
       0  2077.2    15.4 2075.84    31.4 2073.59    42.3 2071.33    47.9 2070.39
    65.4 2066.41    87.2 2063.65   104.7 2061.11   119.6 2056.38   130.2 2054.57
   134.5 2053.31   140.1 2051.92     143 2051.75   177.8 2052.27   182.2 2053.22
   185.5 2054.19   193.6 2056.02   200.6 2058.25   202.5 2059.09   204.2 2059.48
     211 2059.81   218.9 2059.82   230.7 2060.59     236 2061.33   241.3 2062.53
   246.5  2064.4   253.6 2067.57   278.3 2077.28   290.4 2083.31   301.5 2087.68
#Mann= 7 ,-1,0
       0     .07       0      20     .06       0  129.43     .05       0
   134.5    .045       0   182.2     .05       0  219.43     .07       0
  259.43     .05       0
Bank Sta=134.5,182.2
XS Rating Curve= 0 ,0
Exp/Cntr(USF)=0,0
Exp/Cntr=0.3,0.1

Type RM Length L Ch R = 1 ,7182    ,149.7,181.3,226.5
XS GIS Cut Line= 4
2184406.04809464393803.6003693872184311.29290223393781.009727488
2184209.63501368393769.0868887072184121.15499957 393725.16064057
#Sta/Elev= 30
       0 2074.21    10.2 2073.53    26.6 2070.48    34.8  2069.6    38.9 2068.67
    46.7 2066.13    63.6 2062.61    96.7 2060.02   108.6 2058.58   112.6 2057.47
   116.7 2055.74  126.67 2053.17   128.7  2052.4   148.9 2051.26     169 2051.67
   175.8 2053.13   181.1 2054.98   185.1 2057.41   193.8 2061.01   200.8 2065.61
   210.3  2073.3   219.3 2078.26   223.7 2081.78   228.2  2086.3   248.5 2104.48
   254.5 2109.53   259.5 2112.68   268.4 2115.92   280.5 2126.66   298.5 2139.68
#Mann= 3 ,-1,0
       0      .1       0  126.67    .045       0   175.8      .1       0
Bank Sta=126.67,175.8
XS Rating Curve= 0 ,0
Exp/Cntr(USF)=0,0
Exp/Cntr=0.3,0.1

Type RM Length L Ch R = 1 ,7001    ,404.4,400.3,392
XS GIS Cut Line= 4
2184410.88446786 393791.12690636 2184372.4556093393722.408385417
2184376.75808818393597.6364978232184360.02961793393511.157771499
#Sta/Elev= 30
       0 2072.35    43.5 2064.12    57.2 2062.67      71 2060.21    80.3 2059.58
     108 2059.28     112  2058.6     120 2054.25  126.622051.989     132 2050.75
   141.6 2050.54     160 2050.88     164 2052.01     168 2053.43     172 2055.91
     176 2058.88     180 2062.82     184 2065.49     192  2069.2   199.6 2072.04
   204.5 2074.28   216.3 2080.69   232.6 2090.66   238.8    2093   244.8 2095.78
   248.9 2097.91   252.9 2100.89   261.1 2104.55   277.4 2115.95   291.7 2126.41
#Mann= 3 ,-1,0
       0      .1       0  126.62    .045       0     164      .1       0
Bank Sta=126.62,164
XS Rating Curve= 0 ,0
Exp/Cntr(USF)=0,0
Exp/Cntr=0.3,0.1

Type RM Length L Ch R = 1 ,6601    ,310.5,305.6,296.2
XS GIS Cut Line= 2
2184791.39696291393841.847144079 2184724.7916787393468.604713222
#Sta/Elev= 30
       0 2103.35     8.8  2101.4    16.9 2098.07      21  2095.2    25.1 2091.35
    27.5  2090.5    45.4 2089.34    49.4 2088.23    61.6  2079.2    77.9 2071.26
   110.4 2058.47   114.4 2055.74   118.5 2054.14   140.3 2048.62   151.6  2047.5
   179.5 2047.66   184.8 2048.49   187.6 2049.86   203.8 2050.07     216 2051.64
   232.3 2057.97   248.5  2067.7   256.7 2071.21   272.9 2083.22   285.1 2088.42
   301.4 2099.82   317.6 2109.38   325.7 2115.47   344.7 2126.47   379.1 2148.24
#Mann= 5 ,-1,0
       0     .05       0      30     .06       0     130      .1       0
   140.3    .045       0   184.8      .1       0
Bank Sta=140.3,184.8
XS Rating Curve= 0 ,0
Exp/Cntr(USF)=0,0
Exp/Cntr=0.3,0.1

Type RM Length L Ch R = 1 ,6295    ,361,339.9,314.4
XS GIS Cut Line= 3
2185116.34086838393757.1093988742185017.43810795393517.650300867
2184969.34067825393429.312120056
#Sta/Elev= 30
       0 2094.37     8.6 2093.71    17.2 2092.44    21.6  2091.4    25.9 2089.19
    39.9 2079.06    47.5 2074.75    69.2 2067.54    77.8 2063.97    86.5 2061.38
    99.5 2058.42   134.8 2047.01   142.7 2045.91   147.1 2045.75   178.6 2045.55
   190.3  2045.9   199.2    2047   216.3 2048.98     225 2051.29   250.9 2063.77
   259.1  2067.3   268.7 2072.15   278.1 2077.45   305.2 2094.23   310.5 2098.08
   319.3 2105.23   323.4 2107.18   345.4 2119.21   353.7 2123.25   359.7 2125.79
#Mann= 4 ,-1,0
       0     .08       0      50      .1       0   134.8    .045       0
   199.2      .1       0
Bank Sta=134.8,199.2
XS Rating Curve= 0 ,0
Exp/Cntr=0.3,0.1

Type RM Length L Ch R = 1 ,5955    ,368.8,374.4,372.3
XS GIS Cut Line= 3
2185429.36361613 393444.987131572185261.46711269393368.084136668
 2185045.8326429393320.619234209
#Sta/Elev= 30
       0 2104.01     5.7 2101.03    23.3 2093.25    76.2 2072.29    89.3 2064.88
    98.1 2057.73   111.3 2048.66   115.7 2046.21  119.262044.982   124.5 2043.87
   137.7 2043.78   159.7  2044.4   162.8  2044.9   168.5 2046.21   172.9 2046.62
     186 2045.82   206.5 2047.08   222.9 2049.48     231 2051.18   241.9 2052.18
   258.7 2055.28     272 2059.25   284.3 2061.87   296.6 2067.66   308.9 2072.31
   329.3 2083.75     358 2097.89   378.5 2109.53   390.8 2115.47   405.5 2125.57
#Mann= 4 ,-1,0
       0     .06       0      60      .1       0  119.26    .045       0
   162.8      .1       0
Bank Sta=119.26,162.8
XS Rating Curve= 0 ,0
Exp/Cntr(USF)=0,0
Exp/Cntr=0.3,0.1

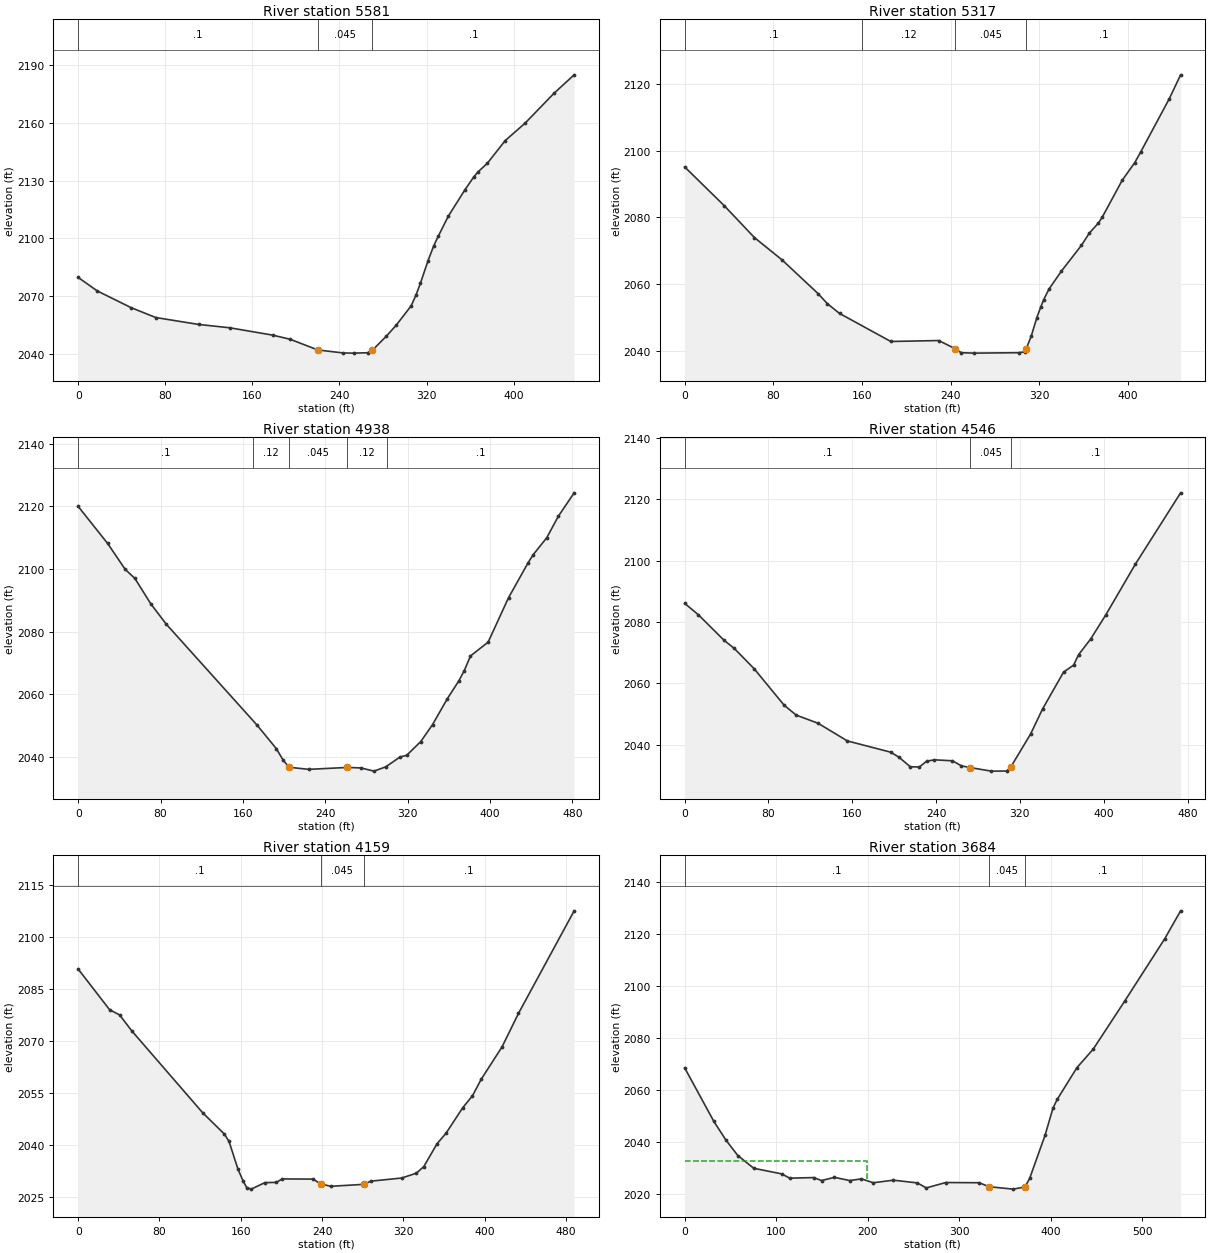
Type RM Length L Ch R = 1 ,5581    ,252.5,264,272.7
XS GIS Cut Line= 4
2185516.63996953393181.521742105 2185385.0589961393045.449106952
2185275.97714048392992.6509174022185134.29556693392961.214325644
#Sta/Elev= 30
       0 2079.73    17.5 2072.72    48.7    2064    71.3 2058.88   110.9 2055.27
   139.2 2053.56   178.5 2049.75   194.7 2047.59   220.1 2042.03   243.6 2040.46
     253 2040.38   265.8 2040.57   270.3 2041.91     283 2049.14     292 2054.81
   305.8 2064.91   310.3 2070.56   314.4 2076.77   321.4 2088.49   326.6 2096.17
   330.8  2101.2     340 2111.59   355.3 2125.33   363.5  2132.1   367.6 2134.78
   375.8 2139.05   392.2 2150.85   410.5 2159.93   437.3  2175.6   455.6 2185.08
#Mann= 3 ,-1,0
       0      .1       0   220.1    .045       0   270.3      .1       0
Bank Sta=220.1,270.3
XS Rating Curve= 0 ,0
Exp/Cntr(USF)=0,0
Exp/Cntr=0.3,0.1

Type RM Length L Ch R = 1 ,5317    ,373,378.6,381.9
XS GIS Cut Line= 2
2185693.62103969 393005.859149892185370.54541508392696.151724789
#Sta/Elev= 30
       0 2095.09    35.7 2083.46      63 2073.87    87.7 2067.24   120.3  2057.1
   128.8 2054.04   139.7 2051.14     186 2042.71   229.2    2043   243.8 2040.59
   249.5 2039.35   261.1 2039.22   301.6 2039.35   306.8  2039.6  308.232040.573
   312.7 2044.32   317.8 2049.89   321.2 2052.98     324 2055.31   328.9 2058.53
     340 2063.85     358 2071.56   365.1 2075.22   373.3 2078.24   376.7 2079.96
   394.7 2091.03   406.1 2096.37   411.4 2099.52   437.2 2115.51   447.5 2122.72
#Mann= 4 ,-1,0
       0      .1       0     160     .12       0   243.8    .045       0
  308.23      .1       0
Bank Sta=243.8,308.23
XS Rating Curve= 0 ,0
Exp/Cntr=0.3,0.1

Type RM Length L Ch R = 1 ,4938    ,388.8,392,385.1
XS GIS Cut Line= 2
2185933.65037732392759.9190526542185629.40488834392386.325170141
#Sta/Elev= 30
       0 2119.99    28.6 2108.16    45.6  2099.9    55.1 2096.97    70.6 2088.82
    85.4 2082.41   173.4 2050.21   192.4 2042.59   199.2 2038.82     205  2036.6
     224 2035.94   261.5 2036.55   274.7 2036.39   287.3 2035.37   298.7 2036.73
   312.7  2039.9   319.1 2040.42   332.8 2044.84   344.2 2050.23   358.4 2058.42
   369.8 2064.25     375 2067.48   381.1  2072.2   398.2  2076.6   418.1 2090.85
   436.9 2101.89     442 2104.58   455.1 2109.94   466.4 2116.84   481.8 2124.35
#Mann= 5 ,-1,0
       0      .1       0     170     .12       0     205    .045       0
   261.5     .12       0     300      .1       0
Bank Sta=205,261.5
XS Rating Curve= 0 ,0
Exp/Cntr=0.3,0.1

Type RM Length L Ch R = 1 ,4546    ,380.6,387.1,390.5
XS GIS Cut Line= 2
2186165.97614956392503.7569219342185891.81126502392117.848581898
#Sta/Elev= 30
       0 2086.08      13 2082.39    37.6 2074.03    47.3  2071.4    66.3 2064.76
    94.9 2052.87   106.4 2049.64   127.4 2046.95   155.3  2041.2   196.5 2037.55
   204.3 2035.95   215.4 2032.77     224 2032.71     231  2034.6   238.4 2035.04
   255.6 2034.72   264.2 2033.07   272.8 2032.49   292.7 2031.35   307.4 2031.38
  311.072032.572   330.2 2043.46   341.6 2051.62   361.7 2063.67   371.2 2065.92
   376.1 2069.38   387.5 2074.44   401.9 2082.27     430 2098.76   473.4 2122.14
#Mann= 3 ,0,0
       0      .1       0   272.8    .045       0  311.07      .1       0
Bank Sta=272.8,311.07
XS Rating Curve= 0 ,0
Exp/Cntr=0.3,0.1

Type RM Length L Ch R = 1 ,4159    ,473.5,475.5,472.7
XS GIS Cut Line= 2
2186457.39537438392365.5398904792186264.06223545391917.285475385
#Sta/Elev= 30
       0 2090.69    30.9 2078.98    40.8 2077.46    52.7 2072.89   122.4 2049.31
   143.9 2043.12   148.5 2040.99   157.2 2033.06   162.5 2029.48   165.9 2027.68
   170.3 2027.25   183.8 2029.13     195 2029.19   200.8 2030.19   231.3 2030.14
   238.6 2028.74   248.7 2028.07   281.2 2028.63   287.9 2029.54   318.4 2030.45
   332.9 2031.85   340.2 2033.75   353.2 2040.33     362 2043.34   378.6 2050.75
   388.1 2054.16   396.8 2058.98   417.2 2068.25   433.4 2077.92   488.2 2107.49
#Mann= 3 ,0,0
       0      .1       0   238.6    .045       0   281.2      .1       0
Bank Sta=238.6,281.2
XS Rating Curve= 0 ,0
Exp/Cntr(USF)=0,0
Exp/Cntr=0.3,0.1

Type RM Length L Ch R = 1 ,3684    ,351.5,348.4,339.8
XS GIS Cut Line= 2
2186898.12603427 392218.484521182186682.57122075391721.152469051
#Sta/Elev= 30
       0 2068.47    31.9 2047.82    45.1 2040.62    58.1 2034.66    75.5 2029.75
   105.9 2027.61   114.8 2025.95   140.9 2026.17   149.6 2025.03   163.7 2026.26
   180.2 2025.03   193.2 2025.67   206.1 2024.18   228.1 2025.17   254.3 2024.12
     264 2022.18   285.3 2024.26   321.8 2024.19   332.7 2022.65   358.9 2021.72
     372 2022.56   377.1 2025.94   393.8 2042.42   402.5 2052.94   407.2 2056.36
   428.7 2068.56   446.5  2075.7     481 2094.26   524.6 2118.21     542    2129
#Mann= 3 ,0,0
       0      .1       0   332.7    .045       0     372      .1       0
#XS Ineff= 2 , 0
          199.77 2032.45
Permanent Ineff=
       F       F
Bank Sta=332.7,372
XS Rating Curve= 0 ,0
Exp/Cntr(USF)=0,0
Exp/Cntr=0.3,0.1

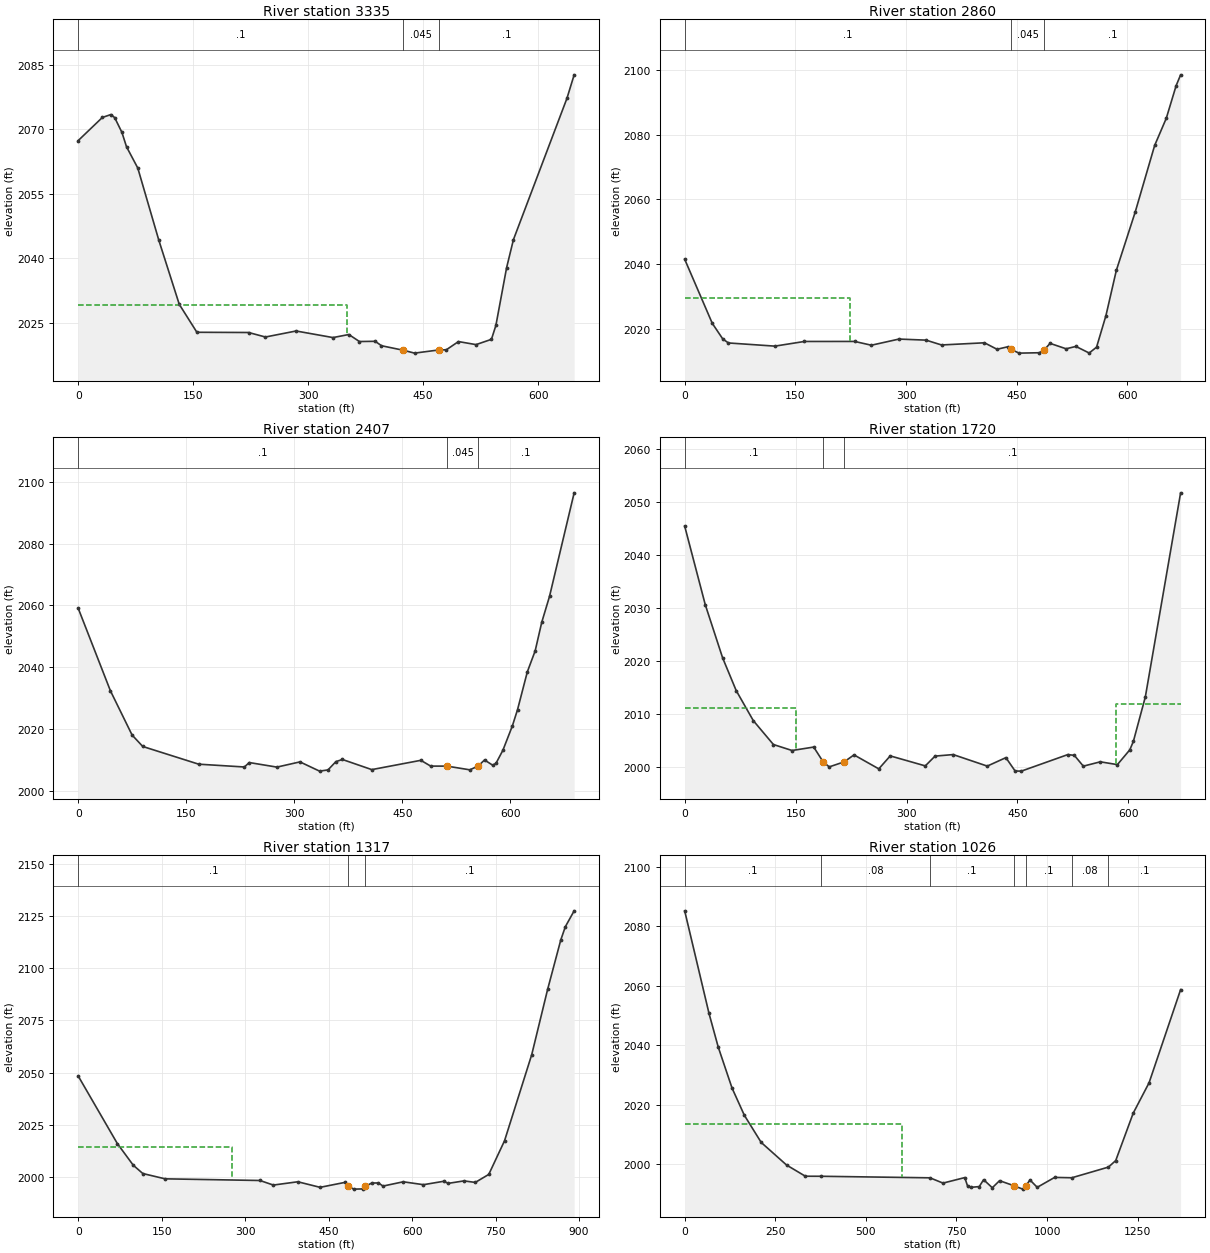
Type RM Length L Ch R = 1 ,3335    ,476.3,475.2,471.4
XS GIS Cut Line= 2
     2187333.329      392123.9312186957.37982601391597.530417648
#Sta/Elev= 30
       0 2067.38    31.5 2072.76    42.7 2073.44    47.6 2072.71      57 2069.29
      63 2065.94    77.7 2060.99   105.2 2044.16   131.8 2029.28   154.8 2022.77
   222.2 2022.72   244.2 2021.67   284.2 2023.07   332.3 2021.54     353 2022.25
   366.8 2020.62   387.4 2020.67   395.6 2019.64   424.3 2018.58   438.7 2017.92
     470 2018.65   480.2  2018.7     496 2020.61   518.9  2019.9     539 2021.13
   544.8 2024.35   558.8 2037.81   567.7 2044.33   637.5 2077.21   646.9 2082.68
#Mann= 3 ,-1,0
       0      .1       0   424.3    .045       0     470      .1       0
#XS Ineff= 2 , 0
           350.2 2029.04
Permanent Ineff=
       F       F
Bank Sta=424.3,470
XS Rating Curve= 0 ,0
Exp/Cntr=0.3,0.1

Type RM Length L Ch R = 1 ,2860    ,460.3,452.9,440.9
XS GIS Cut Line= 2
2187699.66120741391774.3757987652187264.22561505391262.359502229
#Sta/Elev= 30
       0 2041.52    37.4 2021.73    51.6 2016.91    59.3 2015.67   122.3 2014.69
   162.2 2016.13   230.3 2016.14     253 2014.97   290.4 2016.87   327.1 2016.54
   348.1 2015.05   406.3 2015.72   423.3 2013.72   437.5 2014.47   442.6 2013.67
   453.1 2012.53   480.8 2012.65  487.58 2013.62   495.2 2015.54   516.9 2013.87
   530.2  2014.6   548.2 2012.56   558.2 2014.38   570.9 2024.12     585 2038.09
   610.5 2056.04   636.9 2076.64   652.7 2085.05     666 2095.09   672.1 2098.45
#Mann= 3 ,0,0
       0      .1       0   442.6    .045       0  487.58      .1       0
#XS Ineff= 2 , 0
          223.66 2029.65
Permanent Ineff=
       F       F
Bank Sta=442.6,487.58
XS Rating Curve= 0 ,0
Exp/Cntr=0.3,0.1

Type RM Length L Ch R = 1 ,2407    ,679.3,687.1,681.5
XS GIS Cut Line= 2
2188071.63656654 391318.941649312187464.46364291 390994.56289738
#Sta/Elev= 30
       0 2059.06    44.7 2032.34    74.8 2018.02    89.6 2014.32   167.2 2008.59
   230.7 2007.68   237.4 2009.12   275.8 2007.64   307.8 2009.33     335 2006.34
   346.7 2006.73   357.7 2009.42   366.7 2010.11   407.5 2006.83   475.6 2009.84
   489.2 2007.97   511.9 2007.96   543.6 2006.76  555.182007.993     564 2009.95
   575.3 2008.26   579.9 2008.86   589.5  2013.1   602.6 2020.95   609.8 2026.23
   623.4 2038.47   634.3 2045.28   643.4 2054.51   654.2  2062.9   688.4 2096.43
#Mann= 3 ,0,0
       0      .1       0   511.9    .045       0  555.18      .1       0
Bank Sta=511.9,555.18
XS Rating Curve= 0 ,0
Exp/Cntr=0.3,0.1

Type RM Length L Ch R = 1 ,1720    ,412.4,403.5,395.3
XS GIS Cut Line= 2
2188342.71240404390766.9252928752187702.59125222 390566.66498293
#Sta/Elev= 30
       0 2045.47    27.8 2030.63    51.3 2020.56    69.7 2014.36    92.8 2008.69
     120 2004.17   145.2 2003.04   174.5 2003.69   187.1 2000.93   195.5 1999.94
  215.752000.899     229 2002.21   262.5 1999.57     278 2002.02   325.4 2000.13
   338.6 2001.98   363.1 2002.27   409.2 2000.09   434.4 2001.69   446.9 1999.16
   455.3 1999.14   518.2 2002.27     527 2002.12   539.1 2000.08   562.1  2000.9
   585.2 2000.37     602 2003.17   606.8 2004.76     623 2013.18   670.7 2051.76
#Mann= 3 ,0,0
       0      .1       0   187.1    .045       0  215.75      .1       0
#XS Ineff= 2 , 0
          150.54 2011.14   582.8         2011.79
Permanent Ineff=
       F       F
Bank Sta=187.1,215.75
XS Rating Curve= 0 ,0
Exp/Cntr=0.3,0.1

Type RM Length L Ch R = 1 ,1317    ,286.9,291.2,293.9
XS GIS Cut Line= 4
 2188492.3389084390499.5851921582188244.60298322390312.943669171
   2188097.56752390312.2171149142187668.55546469390376.808119115
#Sta/Elev= 30
       0 2048.32    70.3 2015.92    98.9 2005.53   116.1 2001.54   156.1    1999
   326.6  1998.2   350.6 1996.01   394.6 1997.59   434.6 1994.92   478.8 1997.27
485.33911995.498     495 1994.06   511.2 1994.16   515.5 1995.36   527.4 1996.98
   539.5 1997.03   547.6 1995.52     584 1997.58   620.4 1996.19   656.8 1997.83
   664.9 1996.83   693.2 1998.01   713.5 1997.28   737.7 2001.13     766 2017.25
   814.9 2058.59   843.4 2089.86   867.1 2113.62   875.3 2119.97   891.1 2127.57
#Mann= 3 ,-1,0
       0      .1       0485.3391    .045       0   515.5      .1       0
#XS Ineff= 2 , 0
           276.5 2014.48
Permanent Ineff=
       F       F
Bank Sta=485.3391,515.5
XS Rating Curve= 0 ,0
Exp/Cntr(USF)=0,0
Exp/Cntr=0.3,0.1

Type RM Length L Ch R = 1 ,1026    ,256.5,256.5,256.2
XS GIS Cut Line= 4
2188730.36426253390300.6472192242188642.71280826390049.002721485
2187703.99400771390040.5203226852187621.99748598390181.893636021
#Sta/Elev= 30
       0 2085.27    67.2 2050.68    92.6 2039.36   130.7 2025.56   164.6  2016.4
   211.2 2007.23   281.3 1999.61     333 1995.85     377 1995.83   676.9 1995.31
     713 1993.53     773 1995.39     781 1992.44     789 1992.09     813 1992.36
     825 1994.68     849 1991.96     869 1994.35     909 1992.63     933  1991.5
  941.451992.652     953 1994.58     973 1992.11    1021 1995.45  1068.5 1995.33
  1169.4 1998.92  1189.6 2001.12  1237.8 2017.08  1281.7 2027.35  1368.7 2058.73
#Mann= 7 ,-1,0
       0      .1       0     377     .08       0   676.9      .1       0
     909    .045       0  941.45      .1       0  1068.5     .08       0
  1169.4      .1       0
#XS Ineff= 2 , 0
       0     600 2013.59               0
Permanent Ineff=
       F       F
Bank Sta=909,941.45
XS Rating Curve= 0 ,0
Exp/Cntr(USF)=0,0
Exp/Cntr=0.3,0.1

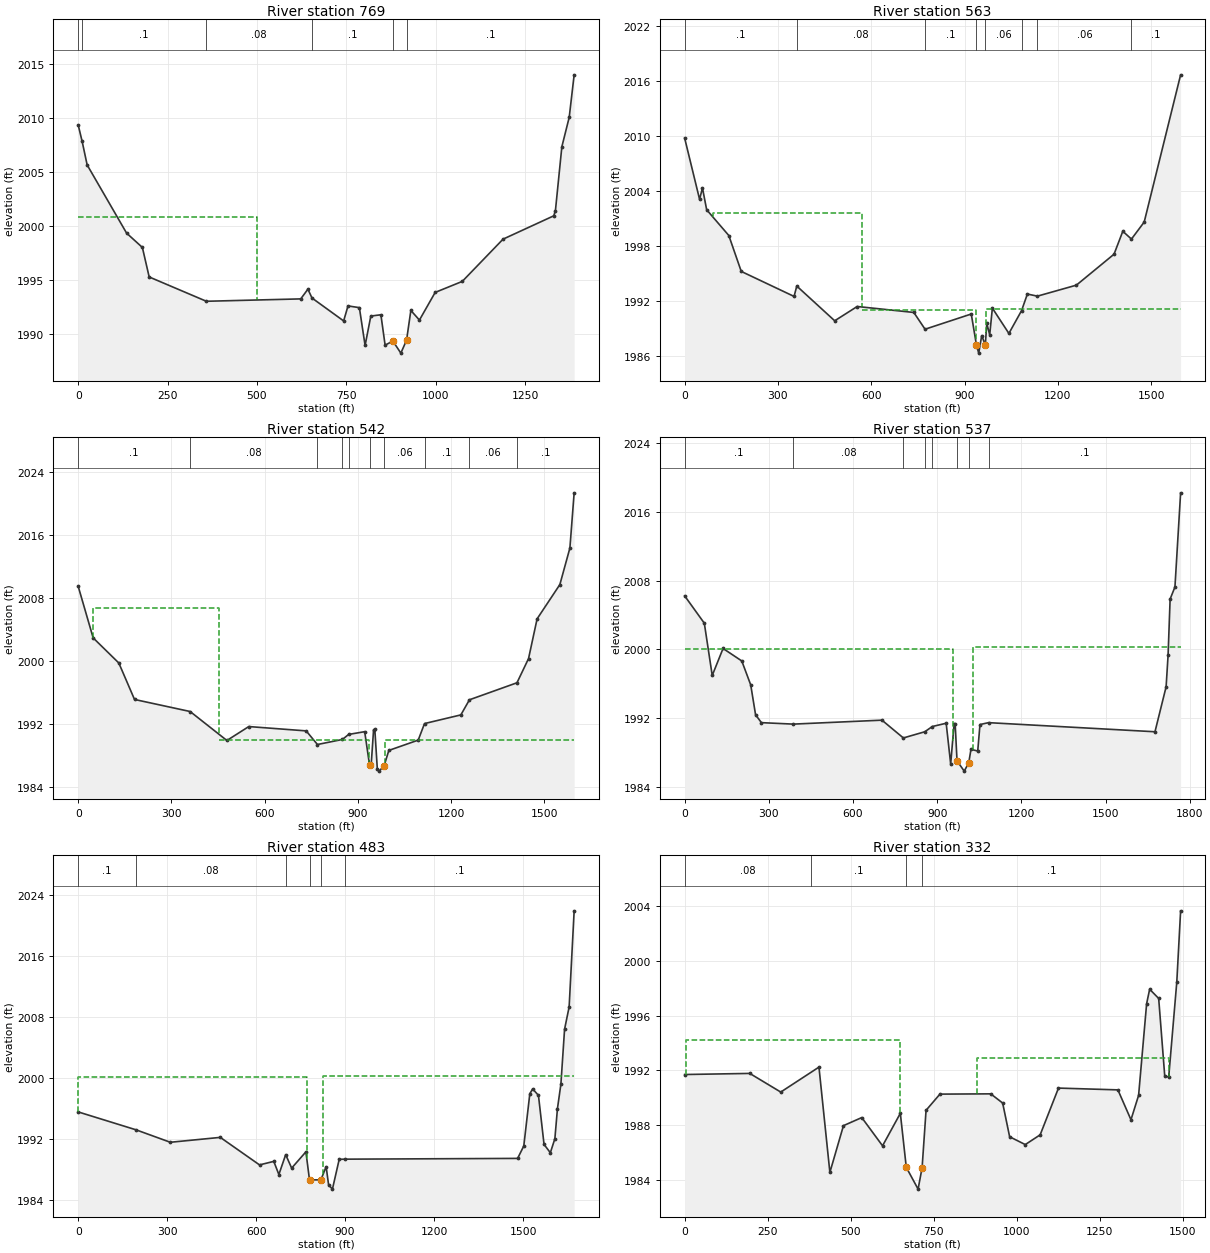
Type RM Length L Ch R = 1 ,769     ,221.2,206.1,199.9
BEGIN DESCRIPTION:
structure xs 4
END DESCRIPTION:
XS GIS Cut Line= 4
2188830.35508449389918.3532092562188692.14271772389787.156449708
2187808.28844384 389790.08247199 2187655.0293226390062.825594101
#Sta/Elev= 30
       0 2009.34    10.9 2007.84      25 2005.65   135.3 1999.34   179.5 1998.01
   198.5 1995.28   358.5 1993.03   622.5 1993.25   642.5 1994.15     654 1993.33
   742.5 1991.21   754.7  1992.6   786.5 1992.44   802.5 1988.94   818.5 1991.66
   846.7 1991.78   858.5 1988.97  880.231989.347   902.5 1988.23   918.5 1989.43
   930.5 1992.18   954.5 1991.29   998.5 1993.85  1074.4 1994.87  1188.4 1998.78
  1330.3 2000.94  1334.9 2001.42  1352.9 2007.33  1373.5 2010.06  1387.3 2013.99
#Mann= 6 ,-1,0
       0    .025       0    10.9      .1       0   358.5     .08       0
     654      .1       0  880.23    .045       0   918.5      .1       0
#XS Ineff= 2 , 0
       0     500 2000.86               0
Permanent Ineff=
       F       F
Bank Sta=880.23,918.5
XS Rating Curve= 0 ,0
Exp/Cntr(USF)=0,0
Exp/Cntr=0.5,0.3

Type RM Length L Ch R = 1 ,563     ,1.6,21,22.8
BEGIN DESCRIPTION:
structure xs 3; 2.6 ft between structure & xs
END DESCRIPTION:
XS GIS Cut Line= 5
2188841.66438549389860.2889364072188415.10617368389613.311443083
2187962.25818296 389572.920497272187890.64429513  389688.2359139
2187384.15619619389759.087352717
#Sta/Elev= 30
       0 2009.79    47.9 2003.12    57.2 2004.36    70.7 2001.98   141.9 1999.17
   181.9 1995.25   351.7 1992.52   360.5 1993.65   482.4 1989.86   554.7 1991.42
   736.8 1990.77   772.9 1988.94   921.5  1990.6938.11661987.235   945.5 1986.33
   955.1 1988.24966.71661987.229   971.4 1989.58   980.8 1988.33   989.4 1991.24
  1042.5 1988.48  1083.3 1990.97  1101.9 1992.78  1134.2 1992.55  1259.5 1993.75
  1380.6 1997.13  1408.8 1999.63  1436.6 1998.78  1477.6 2000.64  1594.7 2016.71
#Mann= 8 ,-1,0
       0      .1       0   360.5     .08       0   772.9      .1       0
938.1166    .045       0966.7166     .06       0  1083.3      .1       0
  1134.2     .06       0  1436.6      .1       0
#XS Ineff= 3 ,-1
   570.2  935.52 1991.08   90.94   570.2 2001.63  969.32  1594.7  1991.2
Permanent Ineff=
       F       F       F
Bank Sta=938.1166,966.7166
XS Rating Curve= 0 ,0
Exp/Cntr(USF)=0,0
Exp/Cntr=0.5,0.3

Type RM Length L Ch R = 1 ,542     ,0.9,4.5,39.8
BEGIN DESCRIPTION:
structure xs 2; 4.1 ft between structure and xs
END DESCRIPTION:
XS GIS Cut Line= 5
2188842.08526388389851.8427038212188415.65352472 389611.88870726
2187942.87637531389569.9059480322187878.40818263389656.499565935
2187358.58865487389723.949804532
#Sta/Elev= 30
       0 2009.48    48.1 2002.94   130.7 1999.75   181.2 1995.12   360.2 1993.59
   478.5 1989.91     549 1991.68   733.7 1991.13   769.9  1989.4   850.2 1990.04
   870.3 1990.68     922 1991.03937.57071986.806   942.6 1986.67   950.6 1991.28
   954.6 1991.31   962.6 1986.31   968.5 1986.02984.58751986.713   999.7 1988.65
  1094.3 1989.96  1114.5 1992.06  1231.5 1993.16  1259.1 1995.08  1412.1 1997.24
  1449.3 2000.31  1476.9 2005.36  1550.1 2009.71  1582.4 2014.35  1596.1 2021.36
#Mann= 10 ,-1,0
       0      .1       0   360.2     .08       0   769.9      .1       0
   850.2     .08       0   870.3      .1       0937.5707    .045       0
984.5875     .06       0  1114.5      .1       0  1259.1     .06       0
  1412.1      .1       0
#XS Ineff= 3 ,-1
  452.23   936.2    1990   49.16  452.23 2006.73  985.96  1596.1    1990
Permanent Ineff=
       F       F       F
Bank Sta=937.5707,984.5875
XS Rating Curve= 0 ,0
Exp/Cntr(USF)=0,0
Exp/Cntr=0.5,0.3

Type RM Length L Ch R = 1 ,537     ,75.8,54.5,53.2
BEGIN DESCRIPTION:
structure xs 3; 15.7 ft between structure and xs
END DESCRIPTION:
XS GIS Cut Line= 6
2188845.12602294 389839.72756664 2188784.0849965389766.874288898
2188664.13170711389691.241090367 2188415.5669245389610.707593073
2187294.35930359389522.8265067242187178.33387358 389607.54190306
#Sta/Elev= 30
       0 2006.22      70 2003.04    98.2 1996.96   136.8  2000.1   203.5 1998.65
   235.4 1995.86   252.7 1992.38   273.6 1991.47   387.2  1991.3   703.1 1991.76
   779.4 1989.69   855.7 1990.41   882.5 1991.02     932  1991.4   948.1 1986.66
   960.1 1991.31   964.1 1991.29  970.681987.026   996.3 1985.83  1012.4 1986.79
  1020.4 1988.36  1044.5 1988.17  1052.5 1991.25  1082.9 1991.47  1676.2 1990.41
  1715.9 1995.64  1722.9  1999.3  1730.2 2005.85  1747.4 2007.26  1767.6 2018.21
#Mann= 8 ,-1,0
       0      .1       0   387.2     .08       0   779.4      .1       0
   855.7     .08       0   882.5      .1       0  970.68    .045       0
  1012.4     .06       0  1082.9      .1       0
#XS Ineff= 2 , 0
             955 2000.09  1027.6         2000.29
Permanent Ineff=
       F       F
Bank Sta=970.68,1012.4
XS Rating Curve= 0 ,0
Exp/Cntr(USF)=0,0
Exp/Cntr=0.5,0.3

Type RM Length L Ch R = 1 ,483     ,165.1,150.9,142.3
BEGIN DESCRIPTION:
structure xs 2; 26.5 ft between structure and xs
END DESCRIPTION:
XS GIS Cut Line= 5
2188712.80857102389658.832127946 2188597.4025269389596.958886182
2188457.30140453389554.3031391192187243.41145479389465.507071445
2187091.58506064389557.990526957
#Sta/Elev= 30
       0 1995.58   194.9 1993.24   310.6 1991.61   479.1 1992.25   611.4 1988.65
   659.5 1989.11   676.6 1987.39   699.6 1989.99   719.7 1988.23   767.8 1990.36
   779.9 1986.69   818.3 1986.69     836 1988.42   844.3 1986.04   857.2 1985.48
   880.1 1989.38   899.9  1989.4  1481.7  1989.5  1502.5 1991.13  1522.8 1997.96
  1532.3 1998.59  1551.9 1997.75  1570.8 1991.33    1592 1990.24  1607.3 1992.08
    1616 1996.02  1627.6 1999.21    1640  2006.4  1655.4 2009.32  1672.3 2021.89
#Mann= 6 ,-1,0
       0      .1       0   194.9     .08       0   699.6      .1       0
   779.9    .045       0   818.3     .06       0   899.9      .1       0
#XS Ineff= 2 , 0
             771 2000.09   824.7         2000.29
Permanent Ineff=
       F       F
Bank Sta=779.9,818.3
XS Rating Curve= 0 ,0
Exp/Cntr(USF)=0,0
Exp/Cntr=0.5,0.3

Type RM Length L Ch R = 1 ,332     ,205.8,206,205.8
BEGIN DESCRIPTION:
structure xs 1
END DESCRIPTION:
XS GIS Cut Line= 5
2188505.76591544389431.7888510282188005.58061081389312.732159251
2187746.35024431389441.8882776512187278.89543504389421.170058957
2187075.59791412389511.812265741
#Sta/Elev= 30
       0  1991.7   196.1 1991.78   289.5 1990.42   404.6 1992.24   437.5 1984.56
   478.4 1987.97   533.6 1988.56   596.2  1986.5   649.8 1988.87   667.7 1984.93
   703.3 1983.34   715.4 1984.91   727.3 1989.09   769.1 1990.27   922.1 1990.29
   958.1 1989.62   979.1 1987.16  1026.2 1986.59  1071.1  1987.3  1126.3 1990.71
  1305.3 1990.58  1344.7  1988.4  1367.7 1990.18  1391.9 1996.87    1401 1997.92
  1428.2 1997.25  1446.4 1991.61  1458.4 1991.51  1482.8 1998.46  1494.3 2003.64
#Mann= 4 ,-1,0
       0     .08       0     380      .1       0   667.7    .045       0
   715.4      .1       0
#XS Ineff= 2 ,-1
     2.7  649.92 1994.19  880.68  1458.5 1992.94
Permanent Ineff=
       F       F
Bank Sta=667.7,715.4
XS Rating Curve= 0 ,0
Exp/Cntr(USF)=0,0
Exp/Cntr=0.3,0.1

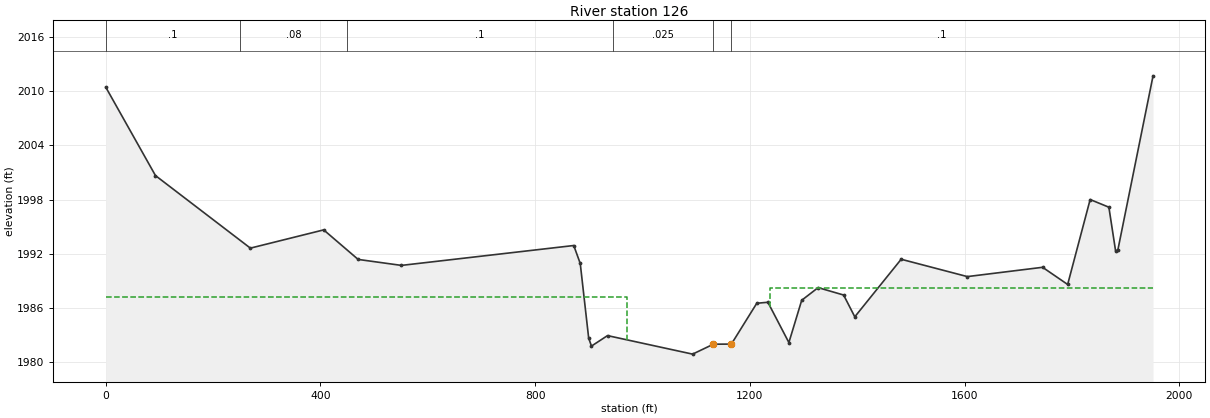
Type RM Length L Ch R = 1 ,126     ,,,
XS GIS Cut Line= 4
2188876.40869435389183.7353290382187975.39824347389100.308435437
2187561.04467192389303.3138765332187010.42717415389500.757524721
#Sta/Elev= 30
       0 2010.45    92.6 2000.67   269.4 1992.64     406 1994.66   470.2 1991.39
   550.8 1990.73   871.9 1992.93     884 1990.94   899.7 1982.68   904.9  1981.8
   934.8 1982.96  1093.3 1980.91  1132.1 1982.01 1165.581982.021  1212.9 1986.54
  1233.6 1986.65  1272.7 1982.19  1296.6 1986.87  1327.2 1988.27  1374.7 1987.45
  1395.5 1985.04  1481.9 1991.41  1605.2 1989.49  1745.4 1990.52  1792.1 1988.62
    1834 1998.02  1868.9 1997.17  1881.4 1992.34  1885.6 1992.43  1951.2 2011.71
#Mann= 6 ,-1,0
       0      .1       0     250     .08       0     450      .1       0
  944.86    .025       0  1132.1    .045       0 1165.58      .1       0
#XS Ineff= 2 , 0
          970.81 1987.22 1238.31         1988.18
Permanent Ineff=
       F       F
Bank Sta=1132.1,1165.58
XS Rating Curve= 0 ,0
Exp/Cntr(USF)=0,0
Exp/Cntr=0.3,0.1
LCMann Table=0

Chan Stop Cuts=-1
Use User Specified Reach Order=0
Composite Channel Slope=5